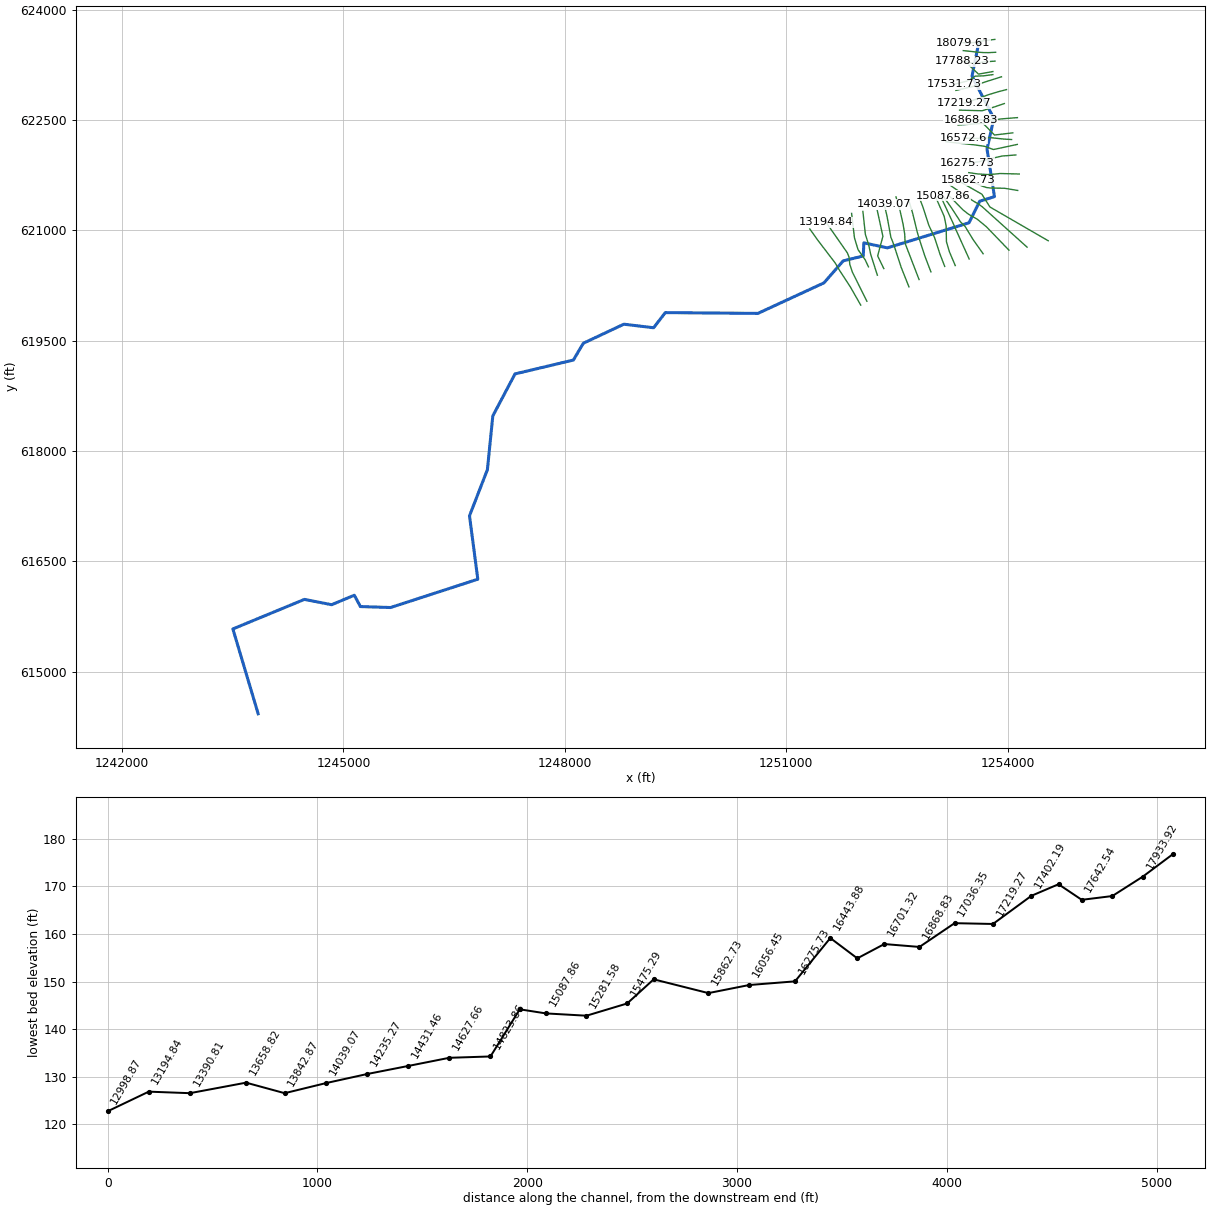
--- 426_ras.prj (project) ---

Proj Title=426
Current Plan=p01
Default Exp/Contr=0.3,0.1
English Units
Geom File=g01
Flow File=f01
Plan File=p01
Y Axis Title=Elevation
X Axis Title(PF)=Main Channel Distance
X Axis Title(XS)=Station
BEGIN DESCRIPTION:
RFD model 426 exported to HEC-RAS
END DESCRIPTION:

--- 426_ras.p01 (plan) ---

Plan Title=Plan 01
Program Version=4.10
Short Identifier=Plan 01
Geom File=g01
Flow File=f01
Subcritical Flow
Calc Critical at every XS
Secant Critical Depth

--- 426_ras.f01 (steady flow) ---

Flow Title=Flow 01
Program Version=5.01
Number of Profiles= 5
Profile Names=10yr,25yr,50yr,100yr,500yr
River Rch & RM=426,87,18079.61
  393.06  470.51  561.37  600.87  707.77
River Rch & RM=426,87,17933.92
  398.12  477.47  569.91  611.17  721.66
River Rch & RM=426,87,17788.23
  404.73  486.55  581.08  624.66  739.89
River Rch & RM=426,87,17642.54
  489.32   604.8  726.86  803.64  986.78
River Rch & RM=426,87,17402.19
  514.53  640.64  771.21  859.03  1064.9
River Rch & RM=426,87,17219.27
  525.08  655.72   789.9  882.49 1098.21
River Rch & RM=426,87,17036.35
  532.12  665.81   802.4  898.23 1120.62
River Rch & RM=426,87,16868.83
  555.44  699.36  844.05  950.86 1195.97
River Rch & RM=426,87,16701.32
  558.44  703.69  849.42  957.68 1205.78
River Rch & RM=426,87, 16572.6
  566.81  715.79  864.45  976.76 1233.28
River Rch & RM=426,87,16443.88
  577.36  731.08  883.46 1000.97 1268.28
River Rch & RM=426,87,16275.73
  582.99  739.26  893.63 1013.95  1287.1
River Rch & RM=426,87,16056.45
  594.47  755.96  914.41 1040.53 1325.72
River Rch & RM=426,87,15862.73
  595.37  757.28  916.05 1042.62 1328.78
River Rch & RM=426,87,15601.89
  602.52  767.71  929.04 1059.28 1353.07
River Rch & RM=426,87,15475.29
  605.61  772.22  934.66 1066.49  1363.6
River Rch & RM=426,87,15281.58
  760.64 1002.76  1222.9 1443.24 1926.85
River Rch & RM=426,87,15087.86
   807.1 1073.26 1311.46 1561.39 2108.16
River Rch & RM=426,87,14963.45
  809.92 1077.57 1316.87 1568.64 2119.36
River Rch & RM=426,87,14823.86
  818.02 1089.93 1332.42  1589.5 2151.59
River Rch & RM=426,87,14627.66
  825.45 1101.29 1346.71 1608.69 2181.32
River Rch & RM=426,87,14431.46
  831.71 1110.85 1358.74 1624.89 2206.43
River Rch & RM=426,87,14235.27
  961.87  1312.3 1612.91 1970.77 2750.95
River Rch & RM=426,87,14039.07
  965.75 1318.37 1620.59 1981.33 2767.81
River Rch & RM=426,87,13842.87
  982.72 1344.95 1654.21 2027.66  2841.9
River Rch & RM=426,87,13658.82
  983.14  1345.6 1655.04  2028.8 2843.73
River Rch & RM=426,87,13390.81
  990.41 1357.03  1669.5 2048.76 2875.73
River Rch & RM=426,87,13194.84
  998.43 1369.62 1685.44 2070.79 2911.11
River Rch & RM=426,87,12998.87
 1015.56 1396.59 1719.61 2118.09 2987.23
River Rch & RM=426,87, 12802.9
 1018.74  1401.6 1725.95 2126.89 3001.41
River Rch & RM=426,87,12606.93
 1101.44 1532.77 1892.38 2359.06  3378.7
River Rch & RM=426,87,12410.96
 1105.65 1539.48  1900.9 2371.02 3398.29
River Rch & RM=426,87,12214.99
 1113.81 1552.52 1917.46 2394.28 3436.42
River Rch & RM=426,87,12019.02
    1120 1562.41 1930.04 2411.96 3465.44
River Rch & RM=426,87,11823.05
 1132.06 1581.71 1954.57 2446.49  3522.2
River Rch & RM=426,87,11627.08
 1134.58 1585.75 1959.71 2453.73 3534.11
River Rch & RM=426,87,11431.11
  1141.6    1597 1974.01 2473.89 3567.33
River Rch & RM=426,87,11235.13
 1146.41 1604.71 1983.82 2487.73 3590.14
River Rch & RM=426,87,11039.16
 1162.92 1631.22 2017.55 2535.38 3668.85
River Rch & RM=426,87,10843.19
 1169.04 1641.06 2030.07  2553.1 3698.17
River Rch & RM=426,87,10647.22
 1175.26 1651.08 2042.84 2571.18  3728.1
River Rch & RM=426,87,10451.25
 1183.18 1663.83 2059.07 2594.18 3766.25
River Rch & RM=426,87,10255.28
 1187.42 1670.66 2067.77 2606.52 3786.73
River Rch & RM=426,87,10059.31
 1188.98 1673.19 2070.98 2611.08  3794.3
River Rch & RM=426,87,9863.338
 1191.94 1677.97 2077.07 2619.72 3808.66
River Rch & RM=426,87,9667.367
 1193.19 1679.98 2079.63 2623.35 3814.69
River Rch & RM=426,87,9471.396
 1200.92 1692.46 2095.53 2645.94 3852.26
River Rch & RM=426,87,9275.425
 1202.46 1694.94 2098.69 2650.43 3859.74
River Rch & RM=426,87,9079.454
  1251.3 1774.09 2199.59 2794.27 4100.06
River Rch & RM=426,87,8883.483
 1252.02 1775.26 2201.09 2796.41 4103.65
River Rch & RM=426,87,8671.473
 1256.49 1782.51 2210.35 2809.65 4125.86
River Rch & RM=426,87,8491.541
 1259.21 1786.94    2216 2817.73 4139.43
River Rch & RM=426,87, 8295.57
 1270.72 1805.68 2239.91 2851.97 4196.97
River Rch & RM=426,87,8099.599
 1276.07 1814.39 2251.02  2867.9 4223.78
River Rch & RM=426,87,7954.375
 1286.38  1831.2 2272.49  2898.7 4275.66
River Rch & RM=426,87,7443.234
 1307.17 1865.17 2315.87 2961.06 4380.94
River Rch & RM=426,87,7062.869
 1312.56 1873.98 2327.14 2977.27 4408.36
River Rch & RM=426,87,6682.504
  1344.2 1925.85 2393.44  3072.9 4570.57
River Rch & RM=426,87,6302.139
  1354.5 1942.77 2415.07 3104.18 4623.79
River Rch & RM=426,87,6111.956
 1355.78 1944.87 2417.76 3108.07 4630.41
River Rch & RM=426,87,5921.774
 1362.02 1955.13 2430.89 3127.07 4662.77
River Rch & RM=426,87,5731.591
 1386.79 1995.95 2483.12 3202.79 4792.05
River Rch & RM=426,87,5427.037
 1388.76  1999.2 2487.29 3208.84 4802.39
River Rch & RM=426,87,4970.861
 1402.09  2021.2 2515.46 3249.77 4872.47
River Rch & RM=426,87,4590.496
 1411.75 2037.17 2535.91 3279.51 4923.47
River Rch & RM=426,87,4400.313
 1412.71 2038.76 2537.94 3282.47 4928.55
River Rch & RM=426,87,4269.232
 1416.06  2044.3 2545.05 3292.82 4946.31
River Rch & RM=426,87,4136.313
 1417.49 2046.68 2548.09 3297.24  4953.9
River Rch & RM=426,87,3940.075
 1419.04 2049.24 2551.37 3302.03 4962.13
River Rch & RM=426,87,3743.837
 1428.53 2064.95 2571.49 3331.35 5012.52
River Rch & RM=426,87,3547.599
 1443.16  2089.2 2602.57  3376.7 5090.58
River Rch & RM=426,87, 3351.36
 1444.43 2091.32 2605.29 3380.67 5097.41
River Rch & RM=426,87,3018.321
 1453.32 2106.07  2624.2  3408.3 5145.06
River Rch & RM=426,87,2762.645
 1455.73 2110.07 2629.33  3415.8 5158.01
River Rch & RM=426,87,2515.954
 1459.84 2116.91  2638.1 3428.62 5180.14
River Rch & RM=426,87,2370.169
 1460.53 2118.05 2639.56 3430.76 5183.83
River Rch & RM=426,87, 2173.93
 1474.45  2141.2 2669.26 3474.22 5258.96
River Rch & RM=426,87,1977.692
 1475.23 2142.51 2670.93 3476.68 5263.22
River Rch & RM=426,87,1781.454
 1487.62 2163.13 2697.39 3515.46 5330.37
River Rch & RM=426,87,1516.546
 1500.17 2184.07 2724.26 3554.89 5398.76
River Rch & RM=426,87,742.2021
 1499.95  2183.7 2723.79  3554.2 5397.56
River Rch & RM=426,87,347.7746
 1499.51 2182.97 2722.85 3552.83 5395.17
Boundary for River Rch & Prof#=426,87,1
Up Type= 0
Dn Type= 2
Boundary for River Rch & Prof#=426,87,2
Up Type= 0
Dn Type= 2
Boundary for River Rch & Prof#=426,87,2
Up Type= 0
Dn Type= 2
Boundary for River Rch & Prof#=426,87,2
Up Type= 0
Dn Type= 2
Boundary for River Rch & Prof#=426,87,2
Up Type= 0
Dn Type= 2

--- 426_ras.g01 (geometry) ---

Geom Title=426
Program Version=4.10

River Reach=426,87
Reach XY= 30
1253610.35250142623564.9157346641253516.18584886 623095.74921006
1253812.01907805 622519.082705961253719.51909325622103.249498755
1253820.35237792621457.4163542391253620.35243508621394.916378647
1253475.35246933621101.5831366331252369.51945236620760.749936789
1252051.18621495620829.0832590911252042.85287887 620650.74997896
1251771.18629038620584.0833399891251510.35302535620284.916769743
1250615.35327733619869.9169190681249361.18698111619880.750285789
1249202.85368845 619674.917018131248799.52047557619723.250348866
 1248250.3539634619464.0837751921248116.18732971619235.750513539
1247325.35422421619047.4172591721247024.52096304618476.584104076
1246951.04335284617745.3033995631246708.68768325617118.251183257
1246821.18762493616256.5847691741245639.52129576615871.584917918
1245230.35475028615884.9182592181245148.68811223616039.084882483
1244841.18819916615909.9182631081244472.85497665615982.418252319
1243503.25203574615580.497384086 1243845.6457085614427.252649829

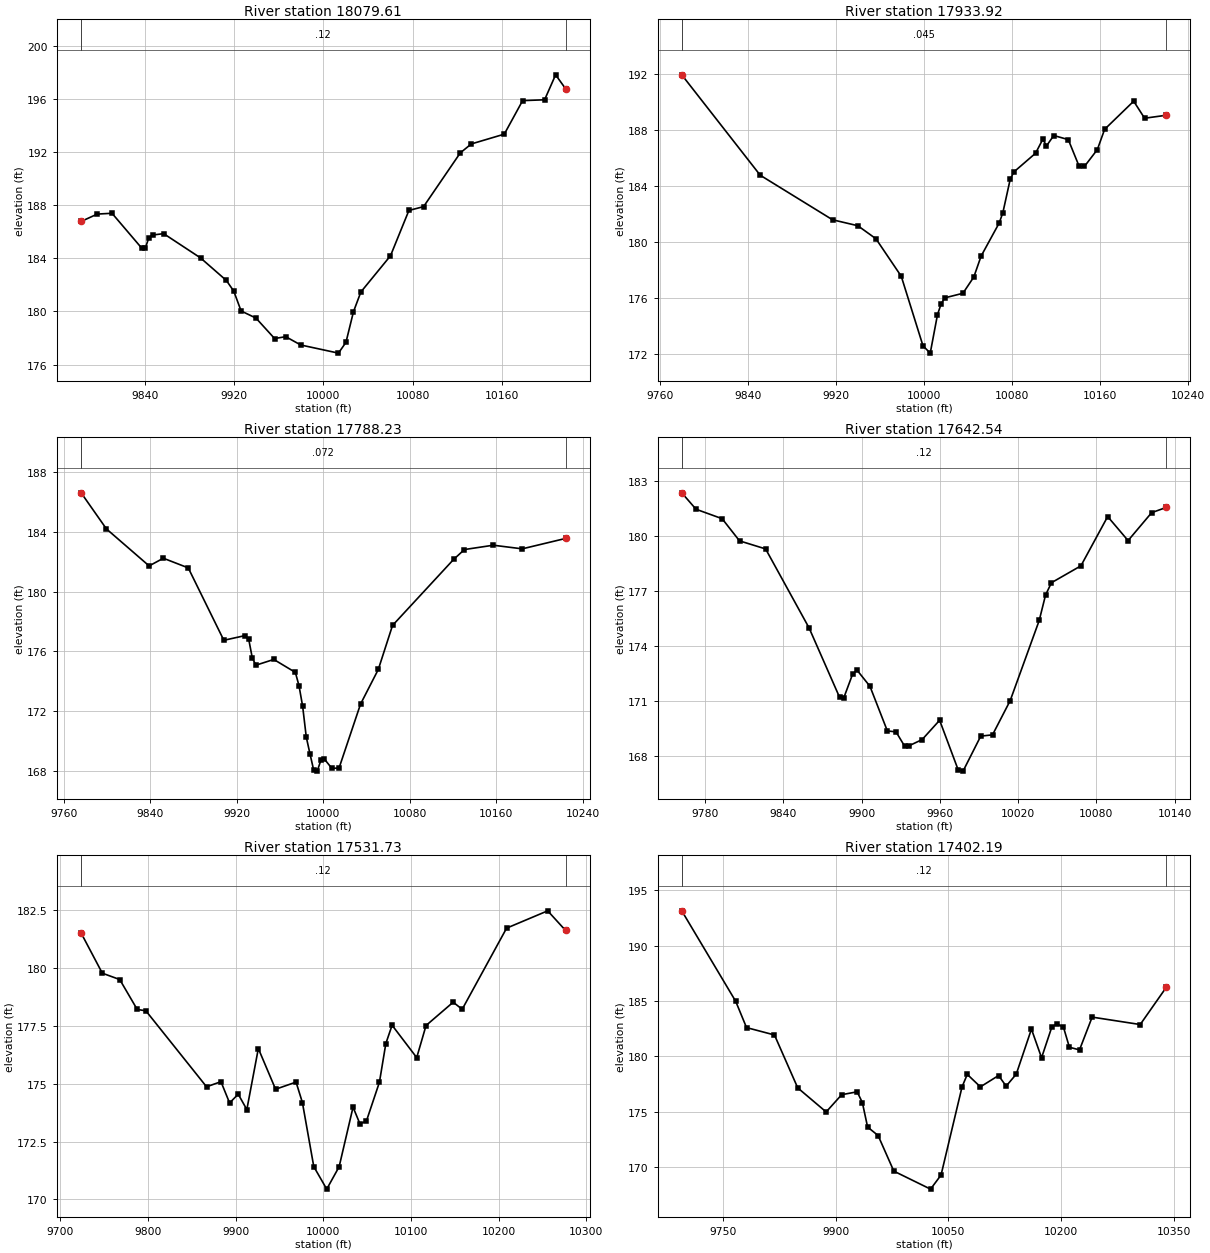
Type RM Length L Ch R = 1 ,18079.61,145.690000,145.690000,145.690000
XS GIS Cut Line= 6
1253825.07777495623594.4656146311253681.93229546623578.280110079
1253585.13957759623558.0087515651253545.44789426623552.365932729
 1253483.6409315623548.8597388611253394.98321709623549.676154256
#Sta/Elev= 30
9783.163186.78539797.586187.34049810.793187.40139837.207184.79179840.508184.7544
 9843.81185.56889847.112185.76169857.017185.86679890.034 184.0379913.147182.3376
 9919.75181.53959926.354180.03769939.669179.50179956.322177.96059966.314178.0994
9979.746 177.47410013.48176.860510020.21177.672210026.94179.981910033.56181.4688
10060.08184.197610076.56187.6143 10089.7187.902210122.56191.953910132.41192.6261
10161.94193.364610178.35195.890210198.03195.954910207.88197.835810216.82196.7869
#Mann= 3 , 0 , 0
9783.163    0.12       09783.163    0.12       010216.82    0.12       0
#XS Ineff= 2 , 0
       0                               0
Bank Sta=9783.163,10216.82
Exp/Cntr=0.3,0.1

Type RM Length L Ch R = 1 ,17933.92,145.689900,145.689900,145.689900
XS GIS Cut Line= 6
1253835.97008463623419.5336195811253744.02305208 623414.88938531
1253670.98070922623415.6837961751253615.28645944623419.517970916
1253604.64728185623420.3334169881253397.51511713623442.229908243
#Sta/Elev= 30
9780.062191.94159851.308184.76789916.954181.58569939.921181.16039956.353180.2305
9979.375177.54839999.108172.578810005.68172.057810012.27174.808610015.57175.5751
10018.87176.005710035.36176.333610045.26177.498810051.86178.988210068.35181.3629
10071.65182.101310078.25 184.46310081.55184.997910101.34186.341610107.94187.3434
10111.24186.860510117.84187.605910131.04187.312610140.93185.397610145.72185.3978
10157.43186.601710164.03188.047510190.42190.057810200.32188.841410219.96189.0519
#Mann= 3 , 0 , 0
9780.062   0.045       09780.062   0.045       010219.96   0.045       0
#XS Ineff= 2 , 0
       0                               0
Bank Sta=9780.062,10219.96
Exp/Cntr=0.3,0.1

Type RM Length L Ch R = 1 ,17788.23,145.689900,145.689900,145.689900
XS GIS Cut Line= 6
1253827.51175123623299.241876788 1253669.6664447623287.815212512
1253585.63874926623271.6915370461253560.08405029623269.489312171
1253509.58384695623274.2599076591253384.19637843623298.125936003
#Sta/Elev= 30
9776.006186.62069799.394184.20139838.867181.72179852.025 182.2369875.051181.5883
9907.945 176.7359927.681177.05159930.971176.8009 9934.26175.55259937.575175.0657
9954.148175.4506 9974.08 174.5839977.449173.69329980.818 172.3129984.187170.2431
9987.555169.13999990.924168.06379994.293167.96399997.662168.6843   10001168.7661
10007.76168.154910014.48168.168310034.34 172.45610050.79174.782410063.93177.7307
10120.39182.154510130.41 182.81810157.13183.108610183.85182.865510223.96183.5629
#Mann= 3 , 0 , 0
9776.006   0.072       09776.006   0.072       010223.96   0.072       0
#XS Ineff= 2 , 0
       0                               0
Bank Sta=9776.006,10223.96
Exp/Cntr=0.3,0.1

Type RM Length L Ch R = 1 ,17642.54,110.804300,110.804300,110.804300
XS GIS Cut Line= 3
1253798.55525699623157.6454369871253603.97324744623122.754869759
 1253477.8304275623242.187965259
#Sta/Elev= 30
9762.194182.37099773.141 181.474 9793.14180.95799806.473179.74729826.472179.3066
9859.803174.99149883.135171.20899886.468171.18419893.135172.46119896.468172.6934
9906.467171.8028  9919.8169.36599926.466169.31349933.133168.52299936.466168.5561
9946.465168.8928 9959.88169.94829974.183167.22279977.841167.16969991.396169.0811
10000.43169.151210013.99171.023210036.22175.397410041.09176.789510045.61177.4614
 10068.2178.383710088.71181.074210104.35179.762110122.42181.287510133.59181.5725
#Mann= 3 , 0 , 0
9762.194    0.12       09762.194    0.12       010133.59    0.12       0
#XS Ineff= 2 , 0
       09942.484                       0
Bank Sta=9762.194,10133.59
Exp/Cntr=0.3,0.1

Type RM Length L Ch R = 1 ,17531.73,129.539900,129.539900,129.539900
XS GIS Cut Line= 6
 1253798.5330221623116.099247488 1253678.3825346623099.839370642
1253557.78629421623094.6064263191253496.74743016623051.763703299
1253444.05020803623026.821546186 1253272.2582128622983.448369215
#Sta/Elev= 30
9723.595 181.5019747.748179.76959767.661179.49539787.575178.20519797.484178.1452
9866.737174.86579883.171175.08579893.026174.16869902.869174.54629912.713173.8817
9925.837 176.5179945.523174.75989968.892 175.0689976.127174.18689989.122171.4195
 10003.9170.447710018.06171.415710033.93173.986710041.79173.265210049.21173.3883
10064.05175.063710071.36176.732310078.49177.5231 10106.6176.125710117.25177.5111
10148.24178.517910158.48178.210110209.19181.713910256.08182.461510276.52181.6131
#Mann= 3 , 0 , 0
9723.595    0.12       09723.595    0.12       010276.52    0.12       0
#XS Ineff= 2 , 0
       09930.871                       0
Bank Sta=9723.595,10276.52
Exp/Cntr=0.3,0.1

Type RM Length L Ch R = 1 ,17402.19,182.920700,182.920700,182.920700
XS GIS Cut Line= 4
1253915.30446267623086.5223576431253687.17383081623014.057333425
  1253522.114609622953.6698132461253298.00981182622901.333962411
#Sta/Elev= 30
9694.997193.14999766.838184.9749 9781.25182.60079818.473181.93429849.455177.1553
9887.321174.97979907.975176.53829928.629176.79949935.531175.82839942.518173.6144
9956.492172.85139977.453169.632610026.36168.007210040.34169.279310068.28177.2372
10075.27178.374510092.74177.246810116.94178.269210127.05177.312510140.53 178.398
10160.74182.464710174.22179.875310187.69182.613610194.43 182.94810203.39182.6372
10211.28180.826310224.75180.5854 10241.6183.547810305.61182.877710340.25186.2306
#Mann= 3 , 0 , 0
9694.997    0.12       09694.997    0.12       010340.25    0.12       0
#XS Ineff= 2 , 0
       0                               0
Bank Sta=9694.997,10340.25
Exp/Cntr=0.3,0.1

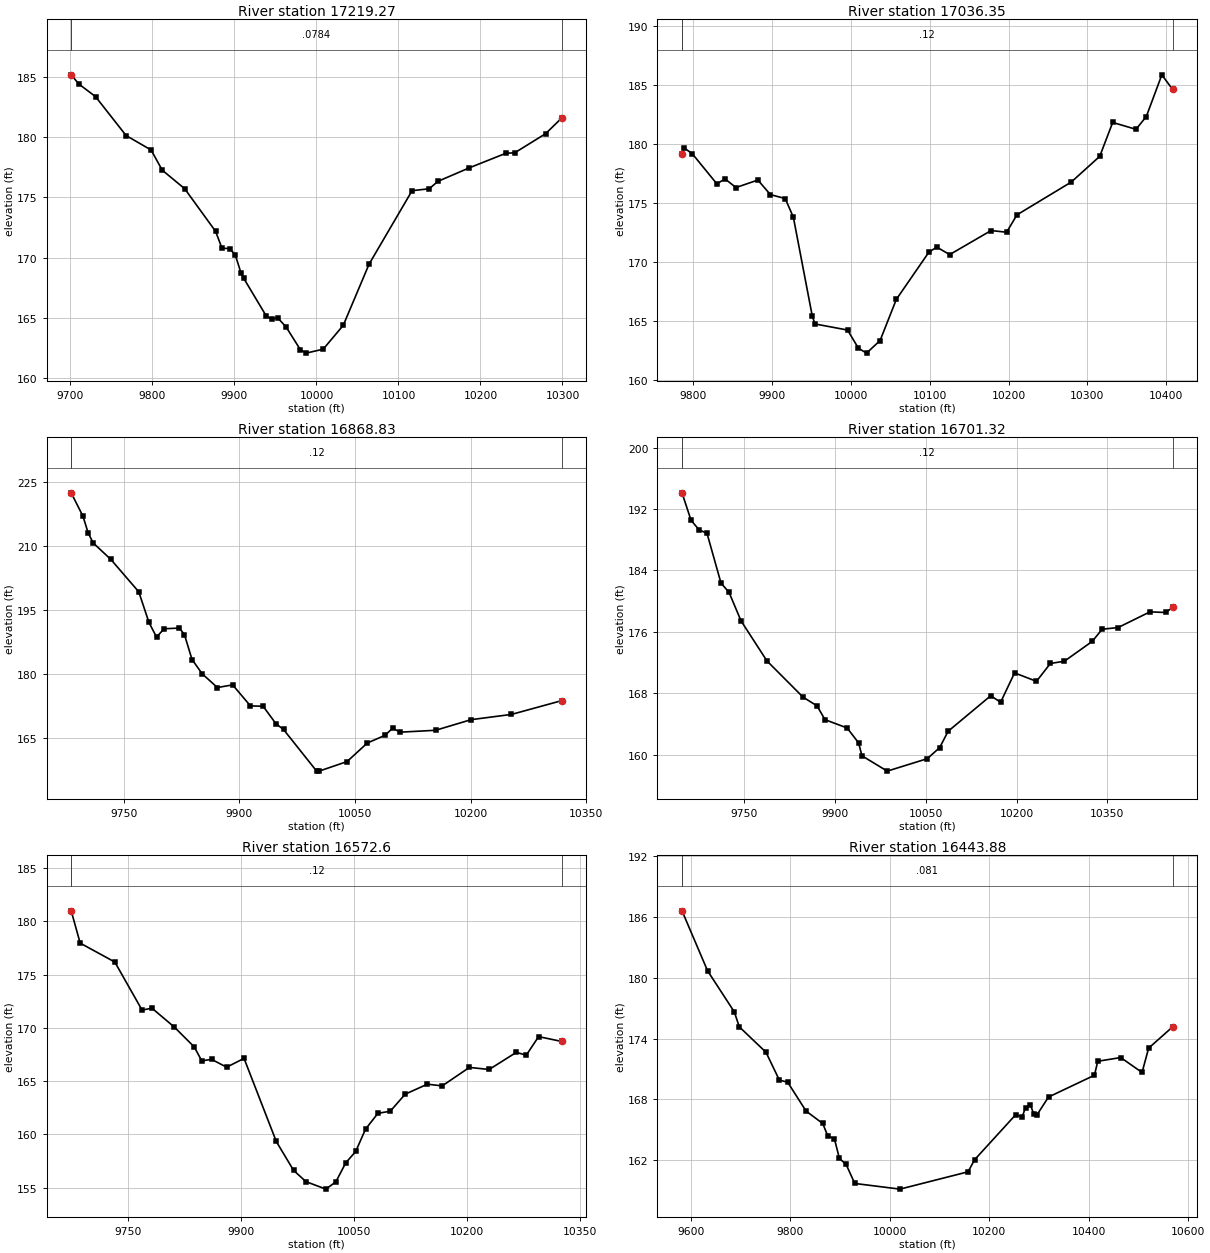
Type RM Length L Ch R = 1 ,17219.27,182.920600,182.920600,182.920600
XS GIS Cut Line= 6
1253983.82015567622912.402460308 1253875.1825895622884.288741418
1253748.51835016 622845.990510411253697.99231656622828.227546258
1253521.34774921622763.2542092991253414.70184684622729.419371621
#Sta/Elev= 30
9700.899185.16029710.229 184.3989730.562183.3553 9767.84180.1284 9798.34  178.93
9811.896177.26019839.302175.71979877.005 172.1859884.736170.78829894.143170.7598
9900.998 170.2329907.853168.7589 9911.28168.2944  9938.7165.17759945.557164.8885
9952.512 165.0299962.945 164.2659980.334162.38169987.289162.093510008.21162.4203
10032.68164.398310064.14169.467310116.58175.556710137.55 175.71810148.03176.3299
10186.49177.454810231.24178.665910241.57178.690310279.43180.2824 10299.1181.5852
#Mann= 3 , 0 , 0
9700.899  0.0784       09700.899  0.0784       0 10299.1  0.0784       0
#XS Ineff= 2 , 0
       0                               0
Bank Sta=9700.899,10299.1
Exp/Cntr=0.3,0.1

Type RM Length L Ch R = 1 ,17036.35,167.517700,167.517700,167.517700
XS GIS Cut Line= 4
1253954.22086459622722.8552916351253825.39415482622678.571110129
 1253653.6252085622624.8933144061253347.66177288 622632.94498378
#Sta/Elev= 30
9785.816179.17049788.353179.67459798.761179.18399829.984176.62439840.392177.0397
9854.269 176.3089882.023176.94569897.973175.70799916.716175.37479927.077173.7845
9951.138 165.3719954.575164.73589995.823164.219910009.57162.677310019.88162.2621
10037.07163.331210057.69166.824610098.94170.824610108.93171.257810125.34170.6202
10177.85172.660610197.54172.518910210.67173.991410279.59176.775310315.69178.9569
 10332.1181.830210361.64181.249510374.77182.334310394.46185.870810408.07184.6356
#Mann= 3 , 0 , 0
9785.816    0.12       09785.816    0.12       010408.07    0.12       0
#XS Ineff= 2 , 0
       0                               0
Bank Sta=9785.816,10408.07
Exp/Cntr=0.3,0.1

Type RM Length L Ch R = 1 ,16868.83,167.517800,167.517800,167.517800
XS GIS Cut Line= 6
1254131.14860546 622531.375078151253939.62424609622516.216498242
1253759.47664676622496.7340833951253717.87064832622496.675116679
1253592.27219502622502.1982219371253496.16013683622501.648800513
#Sta/Elev= 30
9681.603222.41969696.936216.91299703.518213.0899  9710.1210.69569733.138206.8158
 9769.34199.23989782.504192.09119792.377188.64629802.251190.59249821.997 190.756
9828.579189.23399838.453183.39639851.617180.05879871.364176.83329891.165177.4588
9914.276172.53899930.784172.44679947.291168.37719957.196167.016110000.12157.2866
10003.42 157.26510039.68159.5032   10066163.848610088.96165.649710098.81167.3135
10108.66166.386210154.63166.828810200.61169.310910253.12 170.54210318.37173.7693
#Mann= 3 , 0 , 0
9681.603    0.12       09681.603    0.12       010318.37    0.12       0
#XS Ineff= 2 , 0
       0                               0
Bank Sta=9681.603,10318.37
Exp/Cntr=0.3,0.1

Type RM Length L Ch R = 1 ,16701.32,128.718000,128.718000,128.718000
XS GIS Cut Line= 5
 1254068.2861805622324.2976583541253820.02637526622294.774870723
1253714.01272872622404.8143519461253662.70254859622454.433702961
 1253327.2816501622429.836170405
#Sta/Elev= 30
9647.246194.10419662.108190.53839675.324189.2961 9688.54188.82829711.667182.3469
9724.883181.15469744.707177.44219787.658172.21369847.129167.51039870.257166.3724
9883.473164.57359920.088163.48889939.003 161.552 9944.48159.8747 9986.29157.8729
10052.41159.492910072.83160.925410086.99163.068510157.21167.682210173.66166.8474
10196.69170.663610232.87169.5633 10255.9171.889610278.93172.178810324.98174.7631
10341.43176.346410367.75176.565510420.38178.6083 10446.7178.524710457.75  179.19
#Mann= 3 , 0 , 0
9647.246    0.12       09647.246    0.12       010457.75    0.12       0
#XS Ineff= 2 , 0
       0                               0
Bank Sta=9647.246,10457.75
Exp/Cntr=0.3,0.1

Type RM Length L Ch R = 1 , 16572.6,128.718000,128.718000,128.718000
XS GIS Cut Line= 6
1254052.29295011622233.5263600361253950.82668809622239.312604993
1253782.78723472622257.5321859911253754.02594949622256.991905935
1253642.40530205622247.9974498561253402.73500497622252.736106947
#Sta/Elev= 30
9674.394 180.9999686.302177.96819732.308176.18979768.456171.6793 9781.63171.8561
 9811.36170.07949837.787168.21549847.697166.9137 9860.91167.0476 9880.73 166.316
9903.853167.14299946.646159.34359969.616156.62729986.086155.567410012.53154.8658
10025.74 155.55110038.92157.339210052.05158.399610065.19160.504110081.61 161.986
10098.02162.181310117.71163.779310147.24164.720510166.93164.559910203.03166.2945
10229.28166.102210265.37  167.71 10278.5167.441710294.91169.186610325.63168.7315
#Mann= 3 , 0 , 0
9674.394    0.12       09674.394    0.12       010325.63    0.12       0
#XS Ineff= 2 , 0
       0                               0
Bank Sta=9674.394,10325.63
Exp/Cntr=0.3,0.1

Type RM Length L Ch R = 1 ,16443.88,168.146400,168.146400,168.146400
XS GIS Cut Line= 5
1254130.01564556622167.2901058791253806.60692635622097.508971453
1253685.83188596622141.793152884 1253540.9018375622161.922326297
1253162.47337765622203.522617996
#Sta/Elev= 30
9582.032 186.6119633.429180.69029687.131176.6395  9697.2175.15929750.901172.6482
9777.752169.90179794.533169.69149831.453166.84369865.016165.61599875.085164.4017
9888.511164.0974 9898.58162.16169912.005161.57839929.441159.6957 10020.3159.1361
10157.21160.845110170.46162.039910253.03166.482110266.24166.289710272.84167.1924
10282.74167.444910289.34166.554810295.94166.475910319.05168.227810411.46170.3804
10418.06171.759310464.27172.125310507.18170.654310520.38173.053310568.55175.1522
#Mann= 3 , 0 , 0
9582.032   0.081       09582.032   0.081       010568.55   0.081       0
#XS Ineff= 2 , 0
       0                               0
Bank Sta=9582.032,10568.55
Exp/Cntr=0.3,0.1

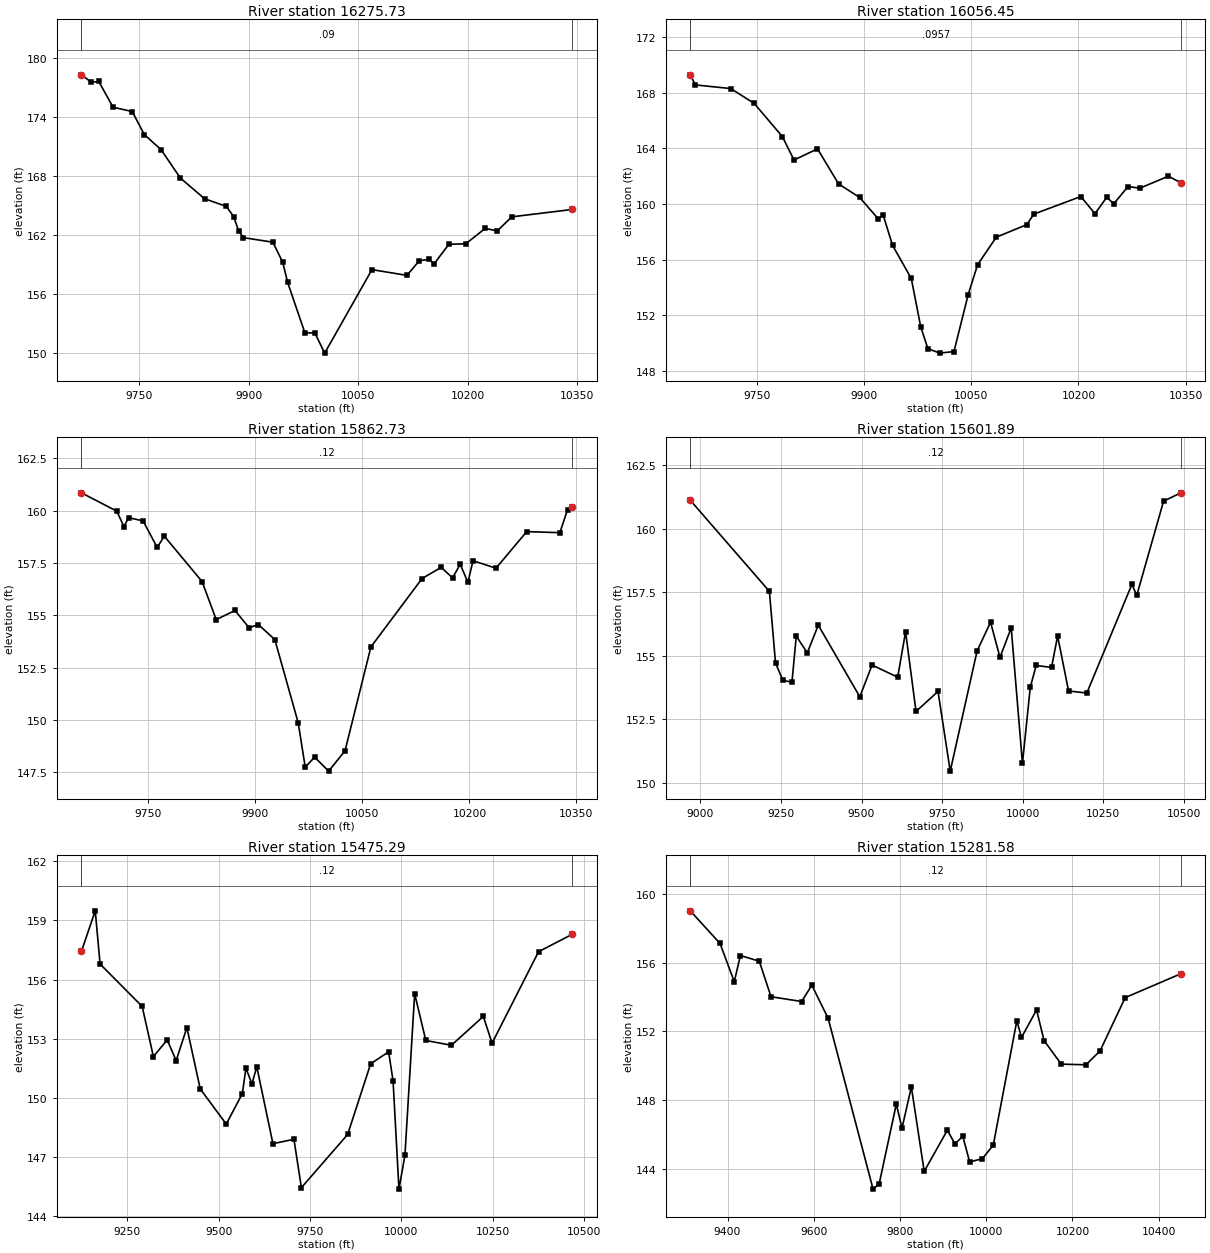
Type RM Length L Ch R = 1 ,16275.73,219.288400,219.288400,219.288400
XS GIS Cut Line= 6
1254109.92292292622023.9533689841253924.86351548622009.179983711
1253765.95975675621973.4937311091253614.14655904621931.733956877
1253536.35247415621920.9816799131253449.28342117621918.297667882
#Sta/Elev= 30
9671.218178.31389684.978177.54859694.832177.6495 9714.54175.02199740.817174.5807
 9757.24172.24919780.276 170.7069806.705167.82619839.742165.72479869.618164.9425
9879.642163.90979886.325162.48059893.007161.76949933.341161.30569946.859 159.264
9953.617157.21249977.273152.08139990.791152.095310004.31150.033710069.06158.5187
10116.98157.934110133.84159.419910147.32159.560210154.07159.0932 10174.3161.0892
10197.63161.147910224.16162.707610240.67162.449810260.46 163.88210343.12164.6299
#Mann= 3 , 0 , 0
9671.218    0.09       09671.218    0.09       010343.12    0.09       0
#XS Ineff= 2 , 0
       0                               0
Bank Sta=9671.218,10343.12
Exp/Cntr=0.3,0.1

Type RM Length L Ch R = 1 ,16056.45,193.717400,193.717400,193.717400
XS GIS Cut Line= 6
 1254155.9924442621764.9255233891253896.79421132621771.567437653
 1253775.8585679621758.7593636331253717.17143211621757.995616547
1253587.72310774621766.5934349311253471.94937425621783.572613189
#Sta/Elev= 30
9656.681169.3043 9664.01168.57579713.277168.31669746.121167.24869785.535164.8589
9801.941163.16779834.749 163.9739864.277161.44719893.805160.46749920.056158.9114
9926.625159.21249939.763157.02269966.038154.63359979.268151.14049989.238149.5819
10005.86 149.25610025.76149.370710045.58153.4587 10058.7155.615210084.95157.6092
10127.64 158.51210137.49159.271110203.29160.537210223.04159.302610239.56160.4803
10249.47160.018410269.31161.2552 10285.9161.138310325.79162.0018 10343.3 161.525
#Mann= 3 , 0 , 0
9656.681  0.0957       09656.681  0.0957       0 10343.3  0.0957       0
#XS Ineff= 2 , 0
       0                               0
Bank Sta=9656.681,10343.3
Exp/Cntr=0.3,0.1

Type RM Length L Ch R = 1 ,15862.73,260.834300,260.834300,260.834300
XS GIS Cut Line= 6
1254134.93430453621541.336760188  1253956.732601621570.983391369
1253771.89467275621574.0359514491253714.15458897621580.514999777
1253656.22439982621599.1571473661253470.30043566621680.715911009
#Sta/Elev= 30
9656.105160.84959705.632 159.9749715.662159.24129722.349159.66199742.411159.5099
9762.301158.24269772.237158.78059825.227156.61159845.034154.79389871.326155.2315
9891.044154.4114 9904.19154.55469927.159153.8454 9959.97149.86919969.813147.7479
9982.938148.230310002.62147.5611 10025.6148.531410061.86153.489810133.54 156.755
 10160.4157.290510176.35156.789210187.09157.438210197.84156.574510205.01157.6078
10237.25157.249510280.24158.996610326.82158.946410337.56 160.053 10343.9160.1553
#Mann= 3 , 0 , 0
9656.105    0.12       09656.105    0.12       0 10343.9    0.12       0
#XS Ineff= 2 , 0
       09880.486        10145.05       0
Bank Sta=9656.105,10343.9
Exp/Cntr=0.3,0.1

Type RM Length L Ch R = 1 ,15601.89,126.600400,126.600400,126.600400
XS GIS Cut Line= 4
 1254548.2137205620857.8302263021253758.85653946621316.238787532
1253649.28571266621490.657654747 1253298.2118389621691.910193786
#Sta/Elev= 30
8968.182161.12469213.957157.53589232.926154.7228 9255.69154.03039284.038153.9613
9297.423155.77679331.569155.11179365.714156.20479494.709153.38479532.648154.6338
9612.321154.15699636.819155.9454 9669.23152.80699737.521153.59549775.461150.4578
9858.928155.19169900.631156.32159929.907154.93599964.777156.09799999.648150.7636
10023.98153.758110042.27154.618510089.95154.540310108.86155.778910142.89153.6126
10199.62153.533910339.54157.810510354.67157.377310437.86 161.08810491.64161.4156
#Mann= 3 , 0 , 0
8968.182    0.12       08968.182    0.12       010491.64    0.12       0
#XS Ineff= 2 , 0
       09860.168        10115.54       0
Bank Sta=8968.182,10491.64
Exp/Cntr=0.3,0.1

Type RM Length L Ch R = 1 ,15475.29,193.717400,193.717400,193.717400
XS GIS Cut Line= 6
1254261.98788717620770.6207927171253655.14876753621319.063808367
1253602.18806827621357.5603371861253538.05893621621394.996460035
1253486.98381254621428.6319224831253219.94696265621611.409178168
#Sta/Elev= 30
9124.782157.42879162.524159.48199175.784156.78419290.896154.63949321.647152.0971
9359.439152.93979383.918151.89519413.294153.5644 9449.83150.45749521.004148.6764
9565.067 150.2229574.859151.51359591.273150.71139604.533151.58199648.734147.6819
9706.195147.90679726.632145.45549853.159148.14949916.172151.73269965.274152.3355
9977.389150.87959993.543145.380310009.92147.098110036.52155.282810067.05152.9129
10137.08152.670210224.47154.131810248.33152.774210375.55157.411410467.29158.2886
#Mann= 3 , 0 , 0
9124.782    0.12       09124.782    0.12       010467.29    0.12       0
#XS Ineff= 2 , 0
       09853.255        10063.77       0
Bank Sta=9124.782,10467.29
Exp/Cntr=0.3,0.1

Type RM Length L Ch R = 1 ,15281.58,193.717400,193.717400,193.717400
XS GIS Cut Line= 6
1254016.01256165620730.3702848851253710.93183357621047.861093894
1253587.10156983621150.3337827181253468.33255321621218.769881874
1253393.59660184621277.381079644 1253180.8370586621494.738106102
#Sta/Elev= 30
9313.538159.02849382.688157.12479415.652154.89679429.858156.42259473.688156.0921
9500.884154.02289571.911153.74269595.587154.69389633.467152.75869737.589 142.809
9751.845143.1271 9791.53147.7669 9804.71146.3602  9826.4148.76429856.167143.8434
9909.882146.24129927.474145.45089945.746145.88139961.612144.39579990.993144.5791
10016.44145.377310071.06152.618810081.86151.651310116.86 153.25310134.18151.4655
10174.06150.093910231.39150.054610263.98 150.86210322.44153.970910451.57155.3615
#Mann= 3 , 0 , 0
9313.538    0.12       09313.538    0.12       010451.57    0.12       0
#XS Ineff= 2 , 0
       09884.035        10096.04       0
Bank Sta=9313.538,10451.57
Exp/Cntr=0.3,0.1

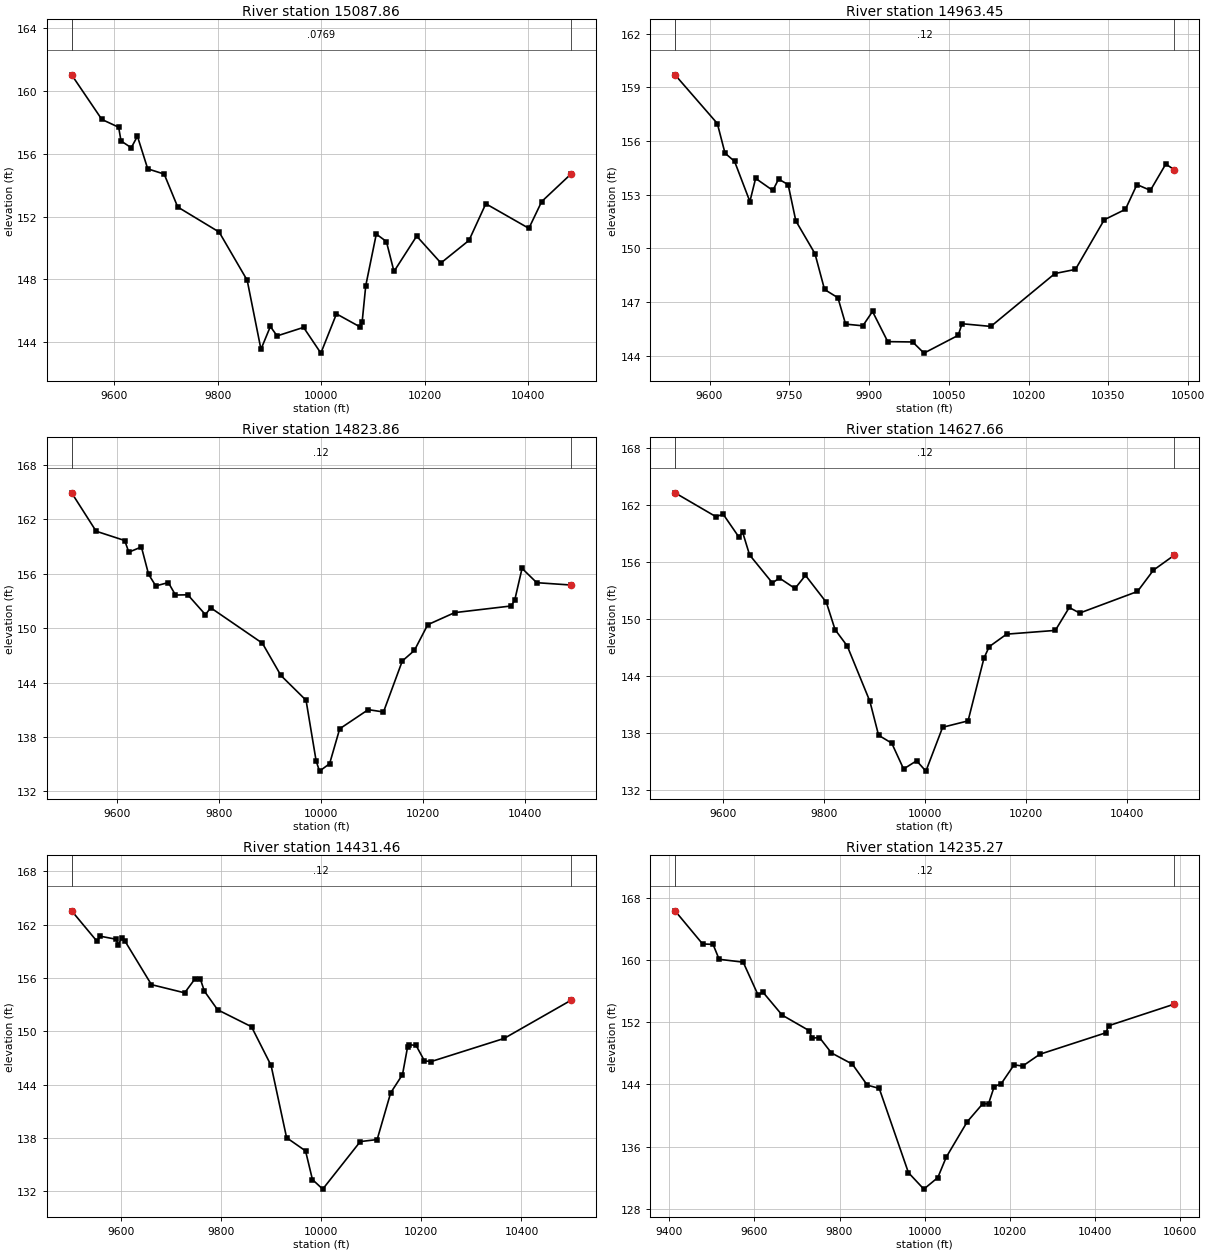
Type RM Length L Ch R = 1 ,15087.86,124.408700,124.408700,124.408700
XS GIS Cut Line= 6
1253666.88438808620680.6061970421253531.21437247620872.669102715
 1253420.7306478621054.7040164351253361.04164869621113.454920165
1253240.03977395621301.4613538211253119.96559556621472.264034765
#Sta/Elev= 30
9517.638161.02839575.992158.18579608.489157.68939613.068156.81539632.835 156.381
9644.763 157.1159664.643155.03769696.451154.70379722.604152.60549802.678 151.008
9856.851147.93679883.458143.53679901.618 144.9919914.612144.39069965.788144.9342
9999.193143.293410029.34145.794410075.07144.961410078.98145.283710085.92 147.589
10106.29150.878910125.79150.406510140.48148.497310184.32150.750310231.14149.0375
10285.41 150.47810317.88152.8126 10401.1151.246210425.87152.952510482.35154.7037
#Mann= 3 , 0 , 0
9517.638  0.0769       09517.638  0.0769       010482.35  0.0769       0
#XS Ineff= 2 , 0
       09862.447        10103.96       0
Bank Sta=9517.638,10482.35
Exp/Cntr=0.3,0.1

Type RM Length L Ch R = 1 ,14963.45,139.591300,139.591300,139.591300
XS GIS Cut Line= 5
 1253477.8304275620609.2920849471253330.21648929620936.726638868
 1253295.3259221621013.2174977811253268.48702419621077.630852669
1253090.00835338621464.110981882
#Sta/Elev= 30
9535.181159.70029614.723156.98019629.118155.32529647.112154.86619675.903152.6223
9686.699153.91569719.089153.24079729.885153.87739747.879153.56439762.274151.5424
9798.263149.71069816.257147.70989841.448147.24649855.844145.77449888.233145.6795
 9906.48146.48069935.099144.79539981.927144.777110003.25144.153610067.55145.1477
10074.77145.795810128.98145.645110249.47148.600710287.99148.829910342.19151.6044
10381.95152.185410403.63153.568410428.93153.247510457.84154.715810473.91154.3971
#Mann= 3 , 0 , 0
9535.181    0.12       09535.181    0.12       010473.91    0.12       0
#XS Ineff= 2 , 0
       0                10099.95       0
Bank Sta=9535.181,10473.91
Exp/Cntr=0.3,0.1

Type RM Length L Ch R = 1 ,14823.86,196.197200,196.197200,196.197200
XS GIS Cut Line= 6
1253289.07704063620520.4661531371253211.23773821620704.051535515
1253169.78376511620843.3815042991253165.56164673621059.647933785
1253139.13441011621189.8440756231253024.36623781621448.785927944
#Sta/Elev= 30
9510.376164.89069558.423160.66319614.526159.63659622.484158.35389647.224158.9303
9661.311155.91379675.398154.6395 9700.05155.00929714.053153.63479738.227153.6604
9772.762151.47379783.122152.23169884.447148.33249920.827 144.7779970.119142.0467
9989.919135.35979996.522134.243210016.32135.060810036.11 138.90610092.13141.0142
10122.01140.758310158.88146.372710182.57147.532210208.77150.366910261.62151.6988
10372.01152.428710379.25153.041410393.74 156.573 10422.5154.995710489.59154.7373
#Mann= 3 , 0 , 0
9510.376    0.12       09510.376    0.12       010489.59    0.12       0
#XS Ineff= 2 , 0
       0                10134.78       0
Bank Sta=9510.376,10489.59
Exp/Cntr=0.3,0.1

Type RM Length L Ch R = 1 ,14627.66,196.197300,196.197300,196.197300
XS GIS Cut Line= 6
1253146.69278388620508.2272223451253082.01070806 620675.42730928
1253009.46111397 620899.324752121252931.06922649621067.900775072
1252852.05956127621313.239314233 1252805.4454054621435.406603264
#Sta/Elev= 30
9505.381163.27349586.485160.75839600.643161.02999632.085158.60059639.072 159.163
9653.047 156.7379698.286153.77939712.081 154.299 9743.12153.19929763.813154.5825
9805.198151.73519822.442148.86429846.583147.14289891.417141.31419908.661137.7424
9934.743136.90769958.246134.18759983.973135.052310002.43133.962410035.57138.5814
10085.94139.254210117.53 145.87610127.87147.071310162.34148.389110258.85148.7834
10286.42151.1962 10307.1150.611610421.59152.8834 10453.2155.128710494.62156.7072
#Mann= 3 , 0 , 0
9505.381    0.12       09505.381    0.12       010494.62    0.12       0
#XS Ineff= 2 , 0
       0                               0
Bank Sta=9505.381,10494.62
Exp/Cntr=0.3,0.1

Type RM Length L Ch R = 1 ,14431.46,196.197200,196.197200,196.197200
XS GIS Cut Line= 6
 1252959.2054298620434.8154814551252877.26300204620649.286017803
1252797.39692747620895.1433190841252774.41155804620975.406036644
 1252713.6030598621226.2311820581252665.50739206621387.107222968
#Sta/Elev= 30
9501.171163.55779551.588160.14489558.648160.70049590.417160.35419593.947159.6913
9601.006160.47019608.066160.12419660.616155.25269726.984154.33049747.795155.9129
9758.184155.91269766.391154.52129792.814152.4263 9860.57150.51719899.717146.1559
9930.696138.02969968.559136.54389982.327133.319410002.88132.242610077.89137.5916
10111.65137.821910138.65143.076310162.28 145.13210172.41148.234110175.79148.4843
10189.29148.422210206.17146.673710219.67146.600610365.13149.194410498.81153.4883
#Mann= 3 , 0 , 0
9501.171    0.12       09501.171    0.12       010498.81    0.12       0
#XS Ineff= 2 , 0
       0                               0
Bank Sta=9501.171,10498.81
Exp/Cntr=0.3,0.1

Type RM Length L Ch R = 1 ,14235.27,196.197300,196.197300,196.197300
XS GIS Cut Line= 6
1252798.90835593 620329.810477711252610.36897961620820.900033202
1252603.68120598620952.3860599891252582.53543802621081.464252077
1252541.02856564621268.2411129951252486.47409977621452.685148419
#Sta/Elev= 30
9413.601166.33089478.252162.07569502.997  162.019517.137160.10049573.698 159.729
9609.004155.46069619.532155.90859665.152152.92449728.319150.93329735.338149.9626
9752.884150.03679780.958148.05919830.088146.61749865.181143.91799893.255143.4947
9961.828132.66249998.001130.544210030.83132.026310050.55134.646510100.07 139.219
10136.57141.536810149.91141.506110163.25143.722910179.93144.110810209.98146.5287
10230.09 146.36610270.31147.882710425.45150.645810432.24151.5602 10586.4154.3337
#Mann= 3 , 0 , 0
9413.601    0.12       09413.601    0.12       0 10586.4    0.12       0
#XS Ineff= 2 , 0
       0                               0
Bank Sta=9413.601,10586.4
Exp/Cntr=0.3,0.1

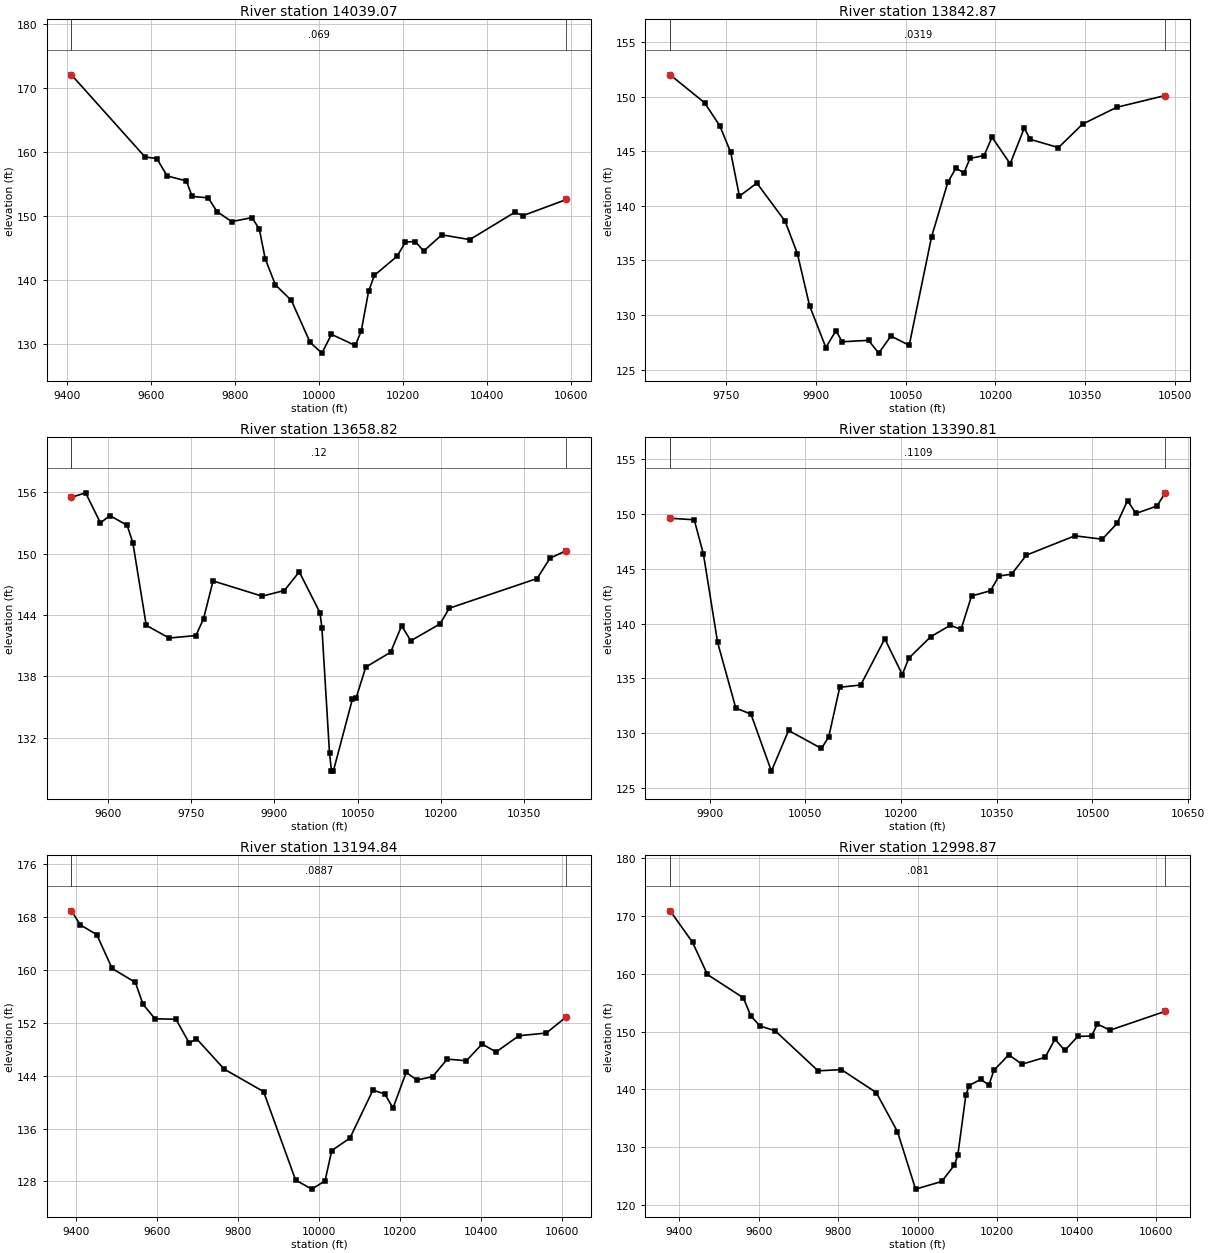
Type RM Length L Ch R = 1 ,14039.07,196.197200,196.197200,196.197200
XS GIS Cut Line= 6
1252661.65999592620230.9159390311252556.54517081620496.201834028
1252452.81208109620814.629721735 1252417.4250339 620904.06365163
 1252361.4342911621206.9462510771252325.54557205621355.861539581
#Sta/Elev= 30
9410.961172.02669586.126159.21839614.182158.97299638.731156.26229684.322155.4848
 9698.33153.07449736.536152.84369757.376150.71339792.109149.14199840.734149.7587
9858.101  147.979871.994143.37219896.306139.28659934.512136.84199978.876130.3151
   10007128.636110029.78131.561110086.61129.825810100.74132.139910118.11  138.28
10131.88140.767910185.84143.733610205.93145.9515 10229.2146.039610249.15144.5516
10292.37147.081210358.86 146.33410465.81 150.58510485.96150.086610588.99152.5912
#Mann= 3 , 0 , 0
9410.961   0.069       09410.961   0.069       010588.99   0.069       0
#XS Ineff= 2 , 0
       0                               0
Bank Sta=9410.961,10588.99
Exp/Cntr=0.3,0.1

Type RM Length L Ch R = 1 ,13842.87,184.054400,184.054400,184.054400
XS GIS Cut Line= 4
1252321.07392964620479.1234303271252237.87334627 620652.23432155
1252308.99642563620917.9394103741252232.50556669621269.528972387
#Sta/Elev= 30
9656.717151.9928 9714.15149.43949739.627 147.3279757.831144.89989772.391140.8862
9801.512142.08499848.784138.58899869.208135.63079889.586130.86289916.757127.0368
9933.738128.58339943.927127.5608 9988.08127.693810005.06126.521910025.44128.0845
10056.01127.239210093.37137.166910120.54142.1599   10134143.453710147.44143.0108
10157.51144.342610181.01144.602710194.44146.281410224.66143.852610248.16147.1121
10258.24146.090310305.24 145.33110345.53147.478110402.61149.021210483.66150.0986
#Mann= 3 , 0 , 0
9656.717  0.0319       09656.717  0.0319       010483.66  0.0319       0
#XS Ineff= 2 , 0
       09945.003                       0
Bank Sta=9656.717,10483.66
Exp/Cntr=0.3,0.1

Type RM Length L Ch R = 1 ,13658.82,268.003700,268.003700,268.003700
XS GIS Cut Line= 5
1252233.84751159620389.2131224871252142.59525886620676.389329612
1252117.09830591620799.848259792 1252071.4721795620944.778308243
1252037.92355719 621256.10952343
#Sta/Elev= 30
9533.977155.53029559.548155.96799586.243153.03069603.455153.73819634.437152.7906
9644.765151.07239668.862143.00479710.172141.75889758.367142.00069772.137143.6443
9789.349147.34439877.684145.85789917.885146.40659944.686148.23959982.075144.2359
9985.515142.78029999.273130.488210002.71128.788910006.15128.735110040.55135.7885
10047.43135.930810064.63138.914410109.34140.3658 10129.3142.9556 10145.8 141.491
 10198.6 143.145 10215.1144.675410373.49147.582310396.59149.564310426.44150.3231
#Mann= 3 , 0 , 0
9533.977    0.12       09533.977    0.12       010426.44    0.12       0
#XS Ineff= 2 , 0
       09952.332                       0
Bank Sta=9533.977,10426.44
Exp/Cntr=0.3,0.1

Type RM Length L Ch R = 1 ,13390.81,195.970900,195.970900,195.970900
XS GIS Cut Line= 5
1252113.07247123620503.2784384191252068.78828973620598.556525826
1251972.16825742620736.7768498211251923.85824129620896.468292087
1251884.94183937621229.270625591
#Sta/Elev= 30
9838.337 149.6119876.019149.4698 9890.49146.32799912.659138.27739941.141132.2824
9964.918 131.7289996.941126.524210023.86130.2361 10075.4128.591210086.85  129.67
10104.03134.181510136.88134.384810174.58138.606310202.01135.338810212.29136.8379
10246.57138.794910277.41139.843810293.98139.4569 10310.5142.512410340.23142.9893
10353.44144.336410373.26 144.50510396.38146.240510472.36148.0059 10515.3147.6972
10538.42149.137210554.94151.215410568.15150.046810601.18150.732410613.96151.9306
#Mann= 3 , 0 , 0
9838.337  0.1109       09838.337  0.1109       010613.96  0.1109       0
#XS Ineff= 2 , 0
       0                               0
Bank Sta=9838.337,10613.96
Exp/Cntr=0.3,0.1

Type RM Length L Ch R = 1 ,13194.84,195.971000,195.971000,195.971000
XS GIS Cut Line= 6
1252091.67265613620035.6955295391251894.81708684620432.357011716
1251861.15357133620534.8805321151251849.88554016620635.701740868
1251827.80225366 620692.34019953 1251537.6534803621110.069466003
#Sta/Elev= 30
 9388.77168.87049410.671166.74389451.263 165.2829489.291160.16269546.627158.0668
9565.659 154.742 9595.18 152.5659646.842152.49899680.054 148.8769697.509 149.572
 9766.04144.96699863.274141.57059942.317128.22139982.131126.845610014.95 128.084
10031.63132.673410076.41 134.54110133.28141.801910162.86141.196710182.88139.0874
 10215.4144.484210241.75 143.31810280.46143.826610317.05146.479510363.95 146.227
10402.84148.756410437.46147.560210493.93  150.0110561.44150.415210611.22 152.881
#Mann= 3 , 0 , 0
 9388.77  0.0887       0 9388.77  0.0887       010611.22  0.0887       0
#XS Ineff= 2 , 0
       0                               0
Bank Sta=9388.77,10611.22
Exp/Cntr=0.3,0.1

Type RM Length L Ch R = 1 ,12998.87,195.970900,195.970900,195.970900
XS GIS Cut Line= 6
1252008.47736409619982.9606096021251869.55422028620227.312799123
1251719.54306829 620458.504322081251662.90067621620554.872819572
1251423.57691417620869.5135206761251318.62471959621018.294168152
#Sta/Elev= 30
9377.025170.89829433.285165.4532 9470.77159.87489561.215155.83169580.241152.6843
9603.071150.95799641.123150.13769749.226143.2025 9808.12143.39919895.685139.4341
9949.165132.66719994.707122.716410060.46124.039210092.28126.882410100.91128.5764
10121.13138.972710129.39140.656710158.49141.706410179.29140.748610191.76143.2833
10229.18145.973510262.45 144.34610320.66145.533810345.48148.670910370.14146.7279
10403.02149.160610437.56149.211310452.08151.2885 10484.2150.237410622.96153.4986
#Mann= 3 , 0 , 0
9377.025   0.081       09377.025   0.081       010622.96   0.081       0
#XS Ineff= 2 , 0
       0                               0
Bank Sta=9377.025,10622.96
Exp/Cntr=0.3,0.1