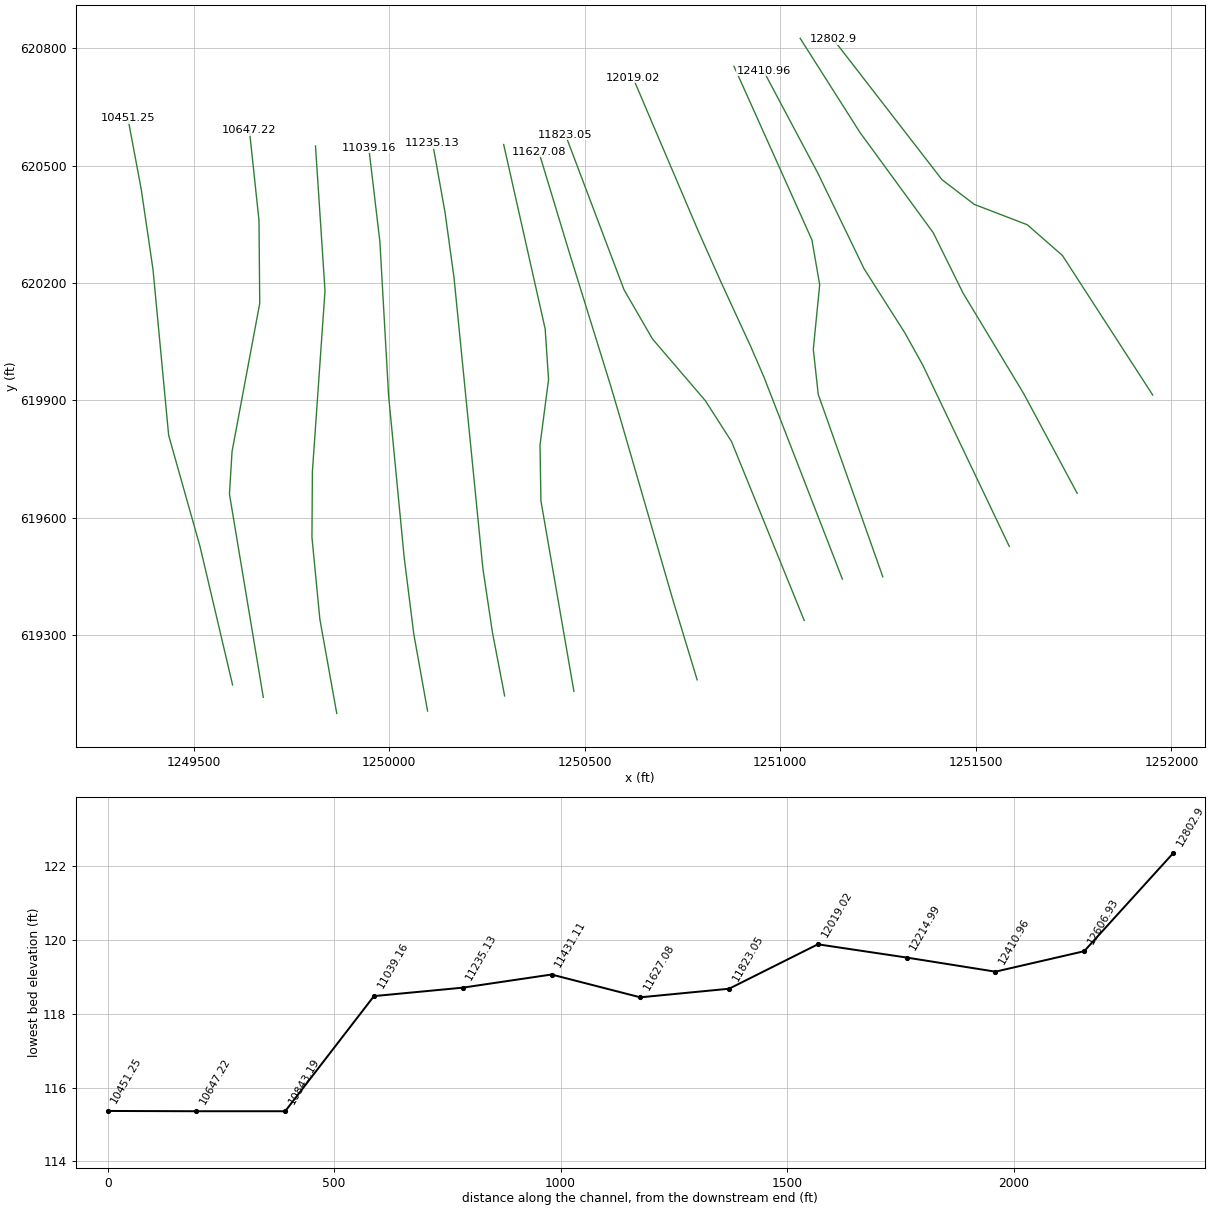
HEC-RAS study 426_ras.prj: 426

--- 426_ras.g01 (geometry) --- (continued)

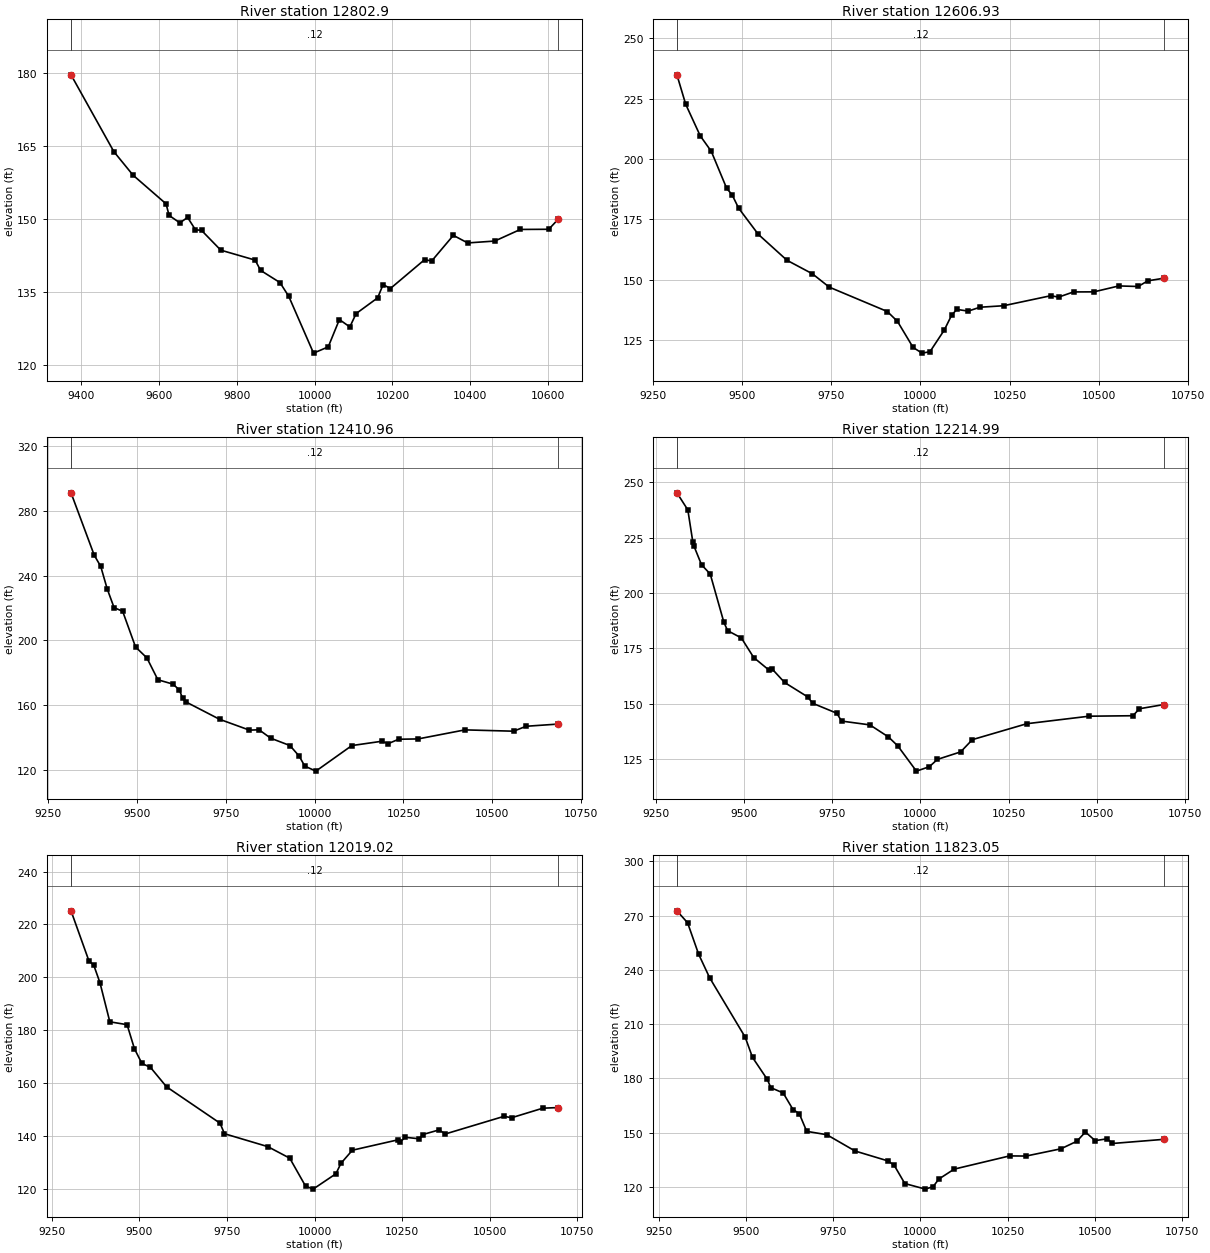
Type RM Length L Ch R = 1 , 12802.9,195.970900,195.970900,195.970900
XS GIS Cut Line= 6
1251952.14470322619913.6971560821251721.34426867620270.178720767
1251631.53107944620348.7174784121251495.64085961 620400.94554398
1251413.41772604620463.926249199 1251135.3830337620822.913796752
#Sta/Elev= 30
9375.018179.5921 9484.92163.79969534.137158.9605 9618.99153.05269626.719150.6825
9654.332 149.1459674.273150.25899694.213147.73979710.166147.58059759.366143.5296
9847.717141.47929861.583139.36899911.285136.86429933.982134.01259997.541122.3453
10035.27123.6327 10063.9129.254610090.68127.731910106.85130.480510162.08133.7146
10176.12136.449810194.77135.632810282.57 141.56910300.79141.294310356.39146.5728
10393.18145.012710462.66145.398910528.39147.787510601.25147.821810625.02 149.845
#Mann= 3 , 0 , 0
9375.018    0.12       09375.018    0.12       010625.02    0.12       0
#XS Ineff= 2 , 0
       0                               0
Bank Sta=9375.018,10625.02
Exp/Cntr=0.3,0.1

Type RM Length L Ch R = 1 ,12606.93,195.971000,195.971000,195.971000
XS GIS Cut Line= 6
1251758.95465483619662.6453753011251622.08331939619917.619785968
 1251467.1506388620174.2841061571251390.88243687620328.555819447
1251203.58974273620584.6657612131251050.73983626620825.170295123
#Sta/Elev= 30
9318.108234.81889342.712222.64089383.465209.56849414.245203.20559457.563187.8279
9472.382185.26179490.907179.67569546.008168.84099626.248158.11329697.563 152.509
9744.678146.99959907.328 136.9079935.764132.82189979.575122.039810004.52119.6961
10026.75120.275810067.04129.289610087.72135.487210102.17137.783810133.78 137.077
10166.64138.6795 10232.9139.300310364.67143.430510387.27 142.88310428.72145.0083
10485.68145.038910555.76147.492110609.76147.258810636.75149.603810681.87150.6829
#Mann= 3 , 0 , 0
9318.108    0.12       09318.108    0.12       010681.87    0.12       0
#XS Ineff= 2 , 0
       0                               0
Bank Sta=9318.108,10681.87
Exp/Cntr=0.3,0.1

Type RM Length L Ch R = 1 ,12410.96,195.970900,195.970900,195.970900
XS GIS Cut Line= 6
1251585.45263208 619526.846251391251364.18498249619990.259481116
1251317.94151964620073.2075502611251214.37820455620235.871943829
1251095.56899261620481.4120540131250956.86066264620742.212977669
#Sta/Elev= 30
9315.206291.10769380.603252.50469398.736 245.6729416.869231.82129436.301220.1594
9460.389217.93529496.655195.86839528.687189.07819559.482175.59099601.827172.9108
 9619.96169.3037 9628.77 164.2679638.094161.93859732.865151.18569816.988144.4732
9844.158144.6824 9876.77139.48579930.913 134.9529956.944128.39239972.577122.2475
10003.88119.141610104.93134.933610189.22137.594710207.44136.1349 10236.6138.8441
10291.27139.037410423.13144.632410559.95 143.81410594.89146.855910684.78148.2128
#Mann= 3 , 0 , 0
9315.206    0.12       09315.206    0.12       010684.78    0.12       0
#XS Ineff= 2 , 0
       0                               0
Bank Sta=9315.206,10684.78
Exp/Cntr=0.3,0.1

Type RM Length L Ch R = 1 ,12214.99,195.971000,195.971000,195.971000
XS GIS Cut Line= 6
1251262.07895709619448.951645471 1251096.8651194 619915.48120507
1251084.32691945620030.5599621011251100.62850443620195.391204369
1251080.76547274620310.0763038221250881.58880641 620753.57926957
#Sta/Elev= 30
9309.666245.17879340.622237.46969354.733223.03889358.261221.01789379.428212.7155
9404.123208.50769442.929186.65259453.513182.94479492.319179.65869527.413170.8104
9569.439165.30399579.945165.59179614.936159.5447 9680.66153.01939694.497150.1616
9762.898145.67449776.464142.12599856.844140.39779909.488134.94399935.786130.9339
 9988.66119.5244 10025.2121.508910048.33124.827310114.12128.211110147.27133.7406
10301.72140.935710478.02144.324310602.53 144.53710620.91147.689810690.32149.5879
#Mann= 3 , 0 , 0
9309.666    0.12       09309.666    0.12       010690.32    0.12       0
#XS Ineff= 2 , 0
       0                               0
Bank Sta=9309.666,10690.32
Exp/Cntr=0.3,0.1

Type RM Length L Ch R = 1 ,12019.02,195.970900,195.970900,195.970900
XS GIS Cut Line= 6
1251158.63138708619443.3181783351250958.02737965619959.708475059
1250923.93057353620038.4327480071250848.39346422620201.986197288
1250790.60247651620331.7496325411250622.98650217620724.975739369
#Sta/Elev= 30
9305.276225.14539356.235206.2594  9370.3204.54159387.882197.94349416.012183.1674
9465.241182.08099486.339172.94389507.437167.45079532.051 165.9159577.763158.5912
9730.505144.82289743.038140.84099866.762135.9572 9929.35131.58629974.316121.0461
9995.986119.882910061.05125.690310075.51129.649110108.04134.603610237.45138.5109
10244.63137.7437   10259139.495810298.28 138.92510308.98140.528810355.35142.2799
10373.18140.7436 10540.8147.4189 10562.2146.880910651.36150.493610694.72150.7319
#Mann= 3 , 0 , 0
9305.276    0.12       09305.276    0.12       010694.72    0.12       0
#XS Ineff= 2 , 0
       0                               0
Bank Sta=9305.276,10694.72
Exp/Cntr=0.3,0.1

Type RM Length L Ch R = 1 ,11823.05,195.970900,195.970900,195.970900
XS GIS Cut Line= 6
1251061.01457489619337.6274632871250875.06289197619794.966250798
1250808.33581809619899.0814448351250673.07936857620056.953079227
1250600.31994558620182.698309586 1250450.3704722620579.086557049
#Sta/Elev= 30
9302.396272.65679332.957266.04759364.547248.69349396.138235.63489497.931202.7805
9518.992191.56029561.113179.44929571.643174.78949606.744171.89719635.092162.6821
9652.905160.4695 9674.28150.64919731.861148.78829812.736139.77419906.403134.3279
9924.578131.96949955.289121.770710014.35118.679310036.56120.098710052.95124.2732
10096.73129.744610255.56137.058910302.73136.978910402.65140.997510448.25145.1686
10472.69 150.28110500.64145.502310535.53146.539110549.41143.925910697.59 146.227
#Mann= 3 , 0 , 0
9302.396    0.12       09302.396    0.12       010697.59    0.12       0
#XS Ineff= 2 , 0
       0                               0
Bank Sta=9302.396,10697.59
Exp/Cntr=0.3,0.1

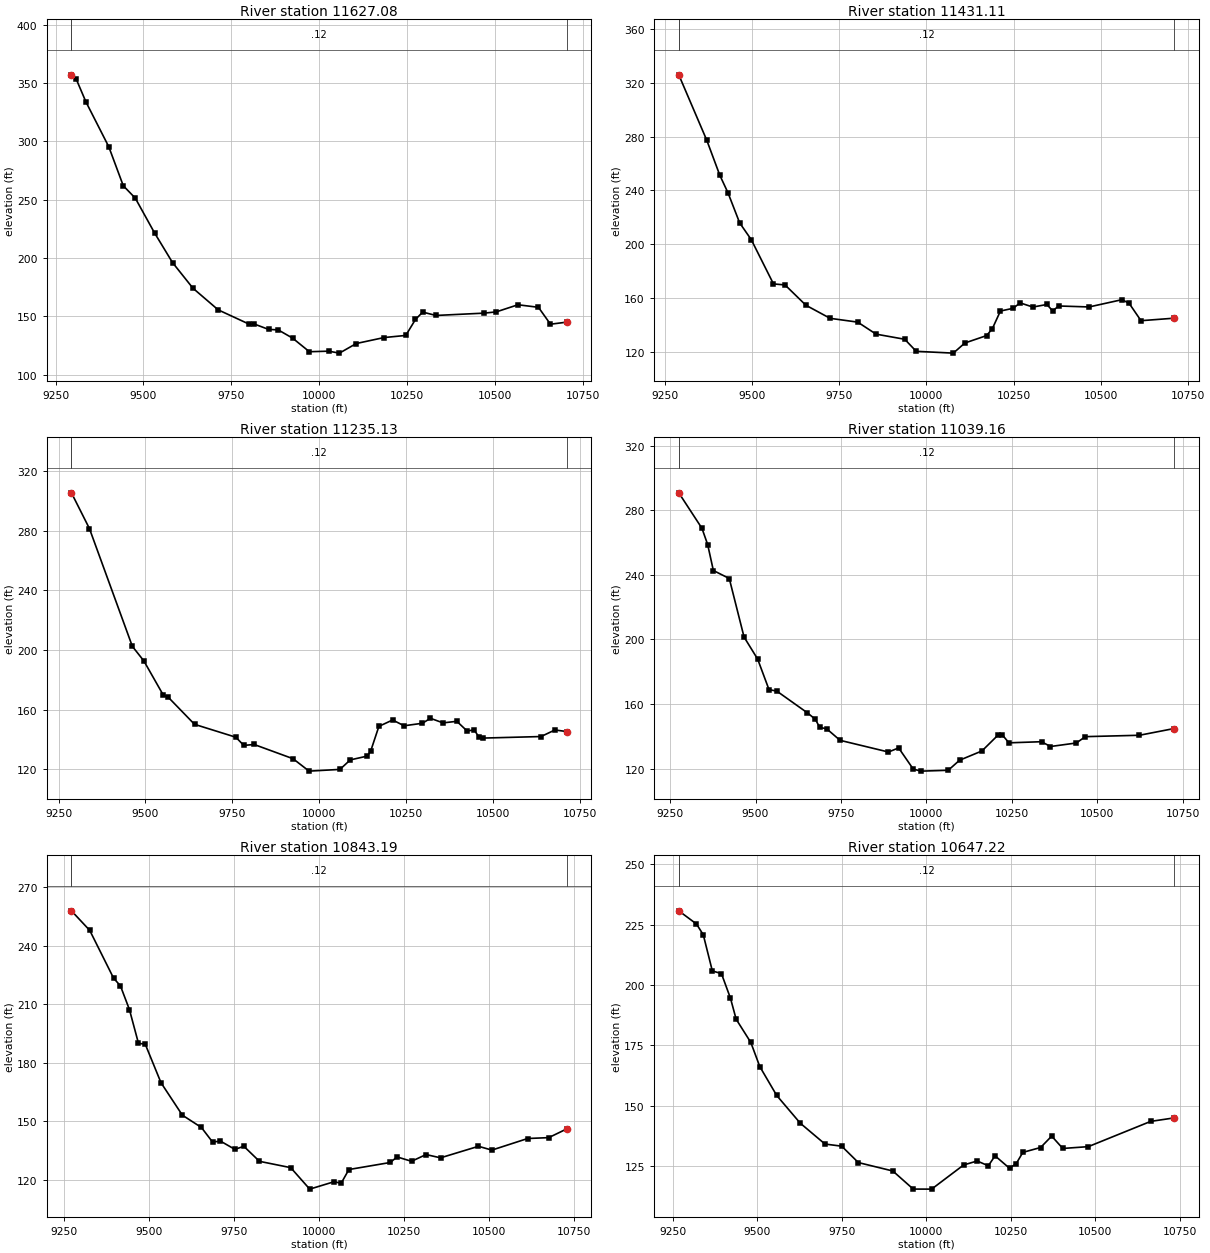
Type RM Length L Ch R = 1 ,11627.08,195.971000,195.971000,195.971000
XS GIS Cut Line= 6
 1250787.3127122619185.6906724611250724.84954203619391.409418036
1250588.71784824619860.882260576     1250565.746619938.529841093
1250460.45656918620277.5218378911250382.22240895620535.796098695
#Sta/Elev= 30
9295.196356.92169308.969353.17259336.399333.76969401.545295.25619442.689261.9046
9476.977251.22279531.756221.44159582.996196.00569641.067174.06839712.803155.5372
9801.618143.17239815.282143.40719856.274 138.7799883.602138.36449924.593131.3146
9972.417119.648410027.12120.123310057.91118.446810105.92126.686710184.93131.7905
10246.77133.607910274.25147.266810294.86153.604410332.65150.7258   10470152.7191
10504.28153.794910565.98159.883910624.26157.724710658.54143.2186 10704.8145.0007
#Mann= 3 , 0 , 0
9295.196    0.12       09295.196    0.12       0 10704.8    0.12       0
#XS Ineff= 2 , 0
       0                               0
Bank Sta=9295.196,10704.8
Exp/Cntr=0.3,0.1

Type RM Length L Ch R = 1 ,11431.11,195.970900,195.970900,195.970900
XS GIS Cut Line= 6
1250472.14018889619156.4644976981250387.82038364619643.200812866
1250385.48459687619785.5792607631250407.31847249619953.148671299
1250398.72664239620082.493952302  1250292.603253620553.787217369
#Sta/Elev= 30
9290.416325.98739370.897277.1644  9407.9251.3609 9431.41238.27079464.814215.9254
9498.217203.38099561.685170.52369594.861169.76299654.577154.68649724.062144.9374
9803.142142.11299855.698133.17789937.805129.36759970.812120.406610077.09119.0646
10109.96126.5764 10172.4132.105610188.89137.270310211.97150.355810248.43152.4024
10268.37156.425410304.97153.331810345.16155.229310361.91150.421710378.66154.1198
10466.14153.398510560.64158.829110580.96156.028110614.82 143.17810709.58145.0415
#Mann= 3 , 0 , 0
9290.416    0.12       09290.416    0.12       010709.58    0.12       0
#XS Ineff= 2 , 0
       0                               0
Bank Sta=9290.416,10709.58
Exp/Cntr=0.3,0.1

Type RM Length L Ch R = 1 ,11235.13,195.970900,195.970900,195.970900
XS GIS Cut Line= 6
1250295.04682082619144.7191870131250263.72733933619307.598501384
1250239.40302469619470.7211391951250165.66312599 620213.07799563
1250142.67759014620379.9081284961250110.86735708620557.762683021
#Sta/Elev= 30
9287.039305.4692 9338.84281.50139462.386202.45619495.558192.66999551.948169.5513
9565.217168.42739641.397150.11619760.241141.47149783.341135.97129813.009136.5872
9925.087127.03259971.212118.708510060.06119.870410089.74126.2335 10139.2128.8309
 10149.1132.530410172.18148.752810211.75153.030110244.73149.142110297.49150.8279
10320.57154.161910356.85151.082210396.56152.144510426.37145.600910446.24146.4249
10459.48141.875210472.73140.8895   10639141.918610678.99  146.3310712.96 145.264
#Mann= 3 , 0 , 0
9287.039    0.12       09287.039    0.12       010712.96    0.12       0
#XS Ineff= 2 , 0
       0                               0
Bank Sta=9287.039,10712.96
Exp/Cntr=0.3,0.1

Type RM Length L Ch R = 1 ,11039.16,195.971000,195.971000,195.971000
XS GIS Cut Line= 6
1250097.98899197619106.1154216831250062.82039122 619302.45140827
1250038.23014305619497.9038999861249998.37247703619911.773414246
1249976.06051326620305.270109527 1249947.6346006620545.948289636
#Sta/Elev= 30
9275.583290.72839343.339268.7782 9360.05258.73779376.714 242.6549423.275237.7023
 9466.51201.47229506.294187.81899539.419 168.9669562.607167.96859651.776154.5607
9674.885150.59919688.062145.49179707.829144.74969747.362137.54379889.022130.3051
9918.672132.85429961.572119.68749984.673118.479910063.82119.004610096.76125.2043
10162.46130.982510208.46140.5892 10221.6141.000210241.31135.997710336.59136.6861
10362.87133.7177 10438.5135.8997 10464.8139.819110623.14140.677910724.39 144.844
#Mann= 3 , 0 , 0
9275.583    0.12       09275.583    0.12       010724.39    0.12       0
#XS Ineff= 2 , 0
       0                               0
Bank Sta=9275.583,10724.39
Exp/Cntr=0.3,0.1

Type RM Length L Ch R = 1 ,10843.19,195.970900,195.970900,195.970900
XS GIS Cut Line= 6
1249865.74440311619100.0720962161249822.54947798619340.850955424
1249802.35261872619550.1595706141249803.46569817619717.613414471
1249835.72632339620180.0869956921249811.39575542620550.017042691
#Sta/Elev= 30
9271.375257.89399325.233 247.8789395.423223.40089415.474219.49619442.046207.3086
9468.618190.02879488.547189.60619534.944169.83829597.709153.24949653.788146.9376
9686.673139.46389709.693139.97089752.387135.71699778.638137.30539824.581129.5979
9916.537 126.3589972.461115.360910044.93119.1911 10064.7118.297810087.76125.4019
10209.63129.011110229.34131.859610272.05129.619610314.72133.062710357.38131.3902
10468.94137.296510508.37135.348810613.67141.286410675.65141.734610728.64146.1964
#Mann= 3 , 0 , 0
9271.375    0.12       09271.375    0.12       010728.64    0.12       0
#XS Ineff= 2 , 0
       0                               0
Bank Sta=9271.375,10728.64
Exp/Cntr=0.3,0.1

Type RM Length L Ch R = 1 ,10647.22,195.971000,195.971000,195.971000
XS GIS Cut Line= 6
1249677.93490113 619141.076440961249591.38097003619660.453830595
1249598.05272432619769.375896799 1249668.8270978620147.776886393
1249666.90002488620359.8450977751249642.47589635620589.852394942
#Sta/Elev= 30
9267.082230.78539319.461225.32039339.587220.85019366.421 205.8399393.256204.7825
 9420.09194.51599436.862185.83079480.225176.20369506.907 166.1629556.938154.1981
9626.841142.6757 9699.77134.05689749.228133.1758 9798.51126.37559900.521122.8821
 9960.89115.382610015.38115.360910110.02125.369710150.03127.030310183.19 125.045
10203.07129.174910245.86 124.01910265.61125.921610285.36130.604610337.88132.6239
 10370.7137.348610403.52132.229410479.02132.978410663.57143.452210732.91144.8995
#Mann= 3 , 0 , 0
9267.082    0.12       09267.082    0.12       010732.91    0.12       0
#XS Ineff= 2 , 0
       09878.051                       0
Bank Sta=9267.082,10732.91
Exp/Cntr=0.3,0.1

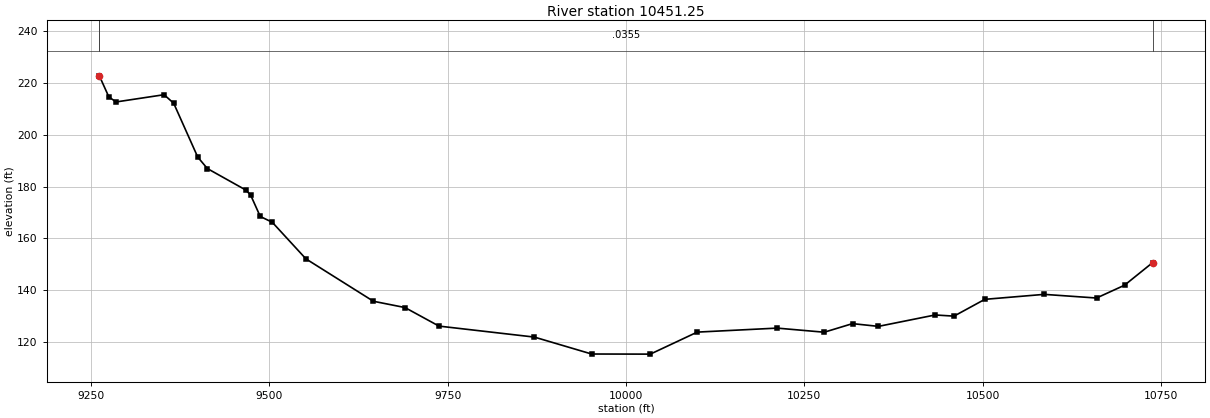
Type RM Length L Ch R = 1 ,10451.25,195.970900,195.970900,195.970900
XS GIS Cut Line= 6
1249599.36303498 619172.828567891249516.36336761619525.713838039
1249435.96894838619810.460284365 1249395.9682992620234.030457495
1249365.98910193620438.2948936751249331.68087607620621.482164144
#Sta/Elev= 30
9261.569222.68089274.839214.5928 9284.95212.60389352.357215.40099365.839212.0936
9399.542191.34239413.024186.92859466.949178.6378 9473.69176.69939487.172168.4489
9504.023 166.2159551.209152.10559645.796135.75379690.055133.33369737.777126.1742
9871.427 121.9429951.767115.414210034.06115.368510099.83123.857510211.88125.4012
 10277.9123.816110317.52127.128810353.85126.070310433.34130.467310459.84130.0204
10503.01136.492410586.22138.412310659.65 137.00310698.87141.932310738.47150.6937
#Mann= 3 , 0 , 0
9261.569  0.0355       09261.569  0.0355       010738.47  0.0355       0
#XS Ineff= 2 , 0
       09877.479                       0
Bank Sta=9261.569,10738.47
Exp/Cntr=0.3,0.1