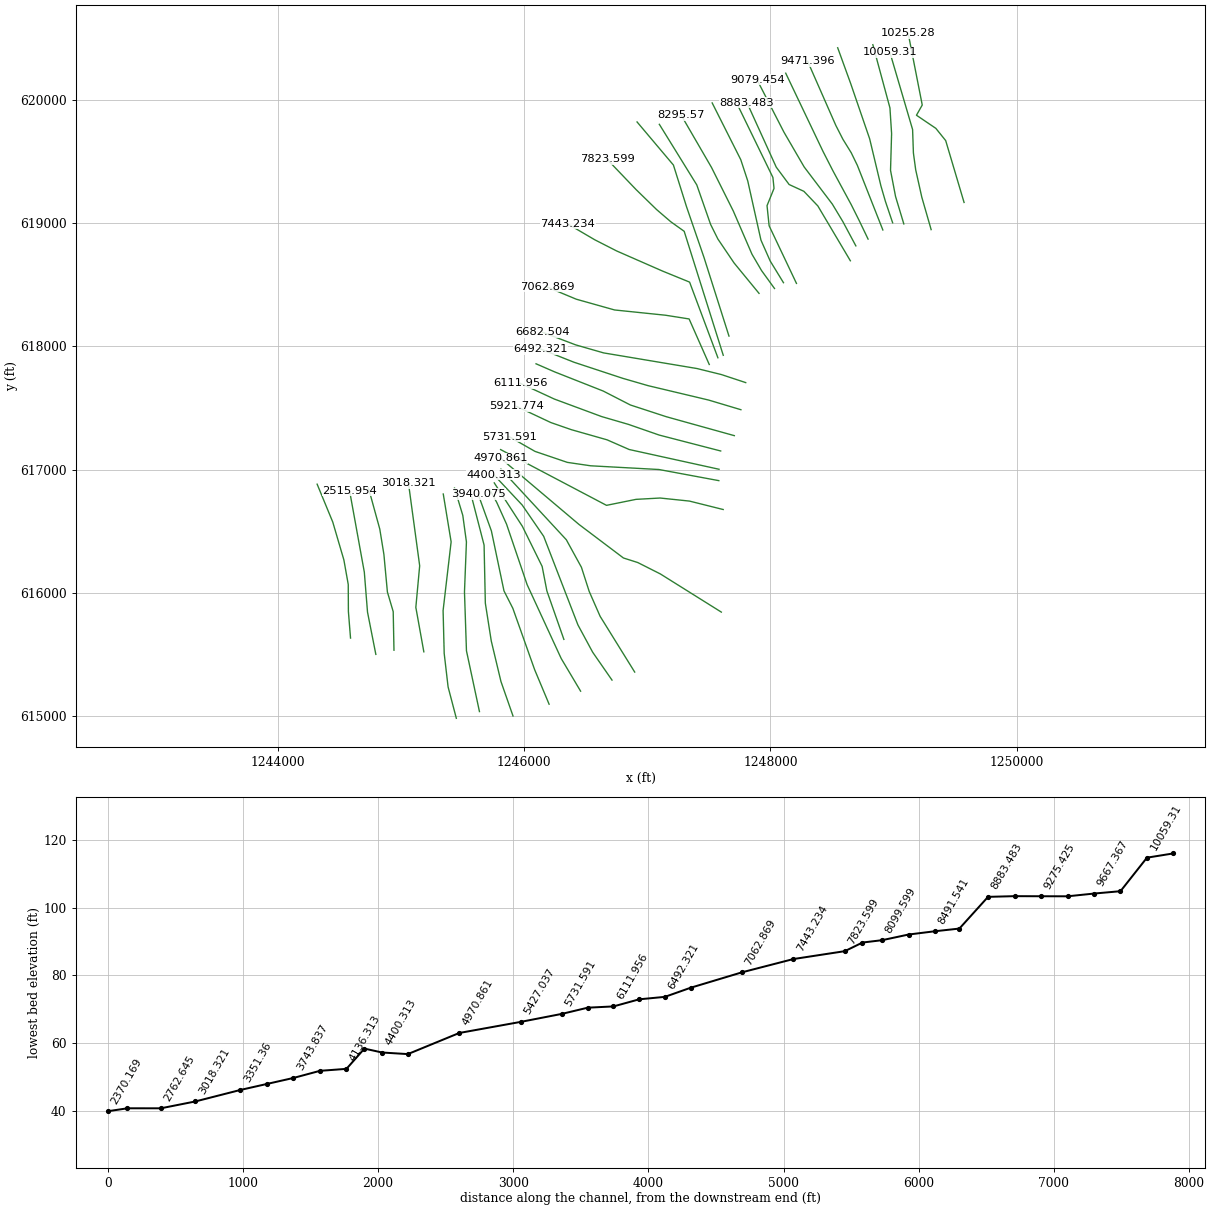
HEC-RAS study 426_ras.prj: 426

--- 426_ras.g01 (geometry) --- (continued)

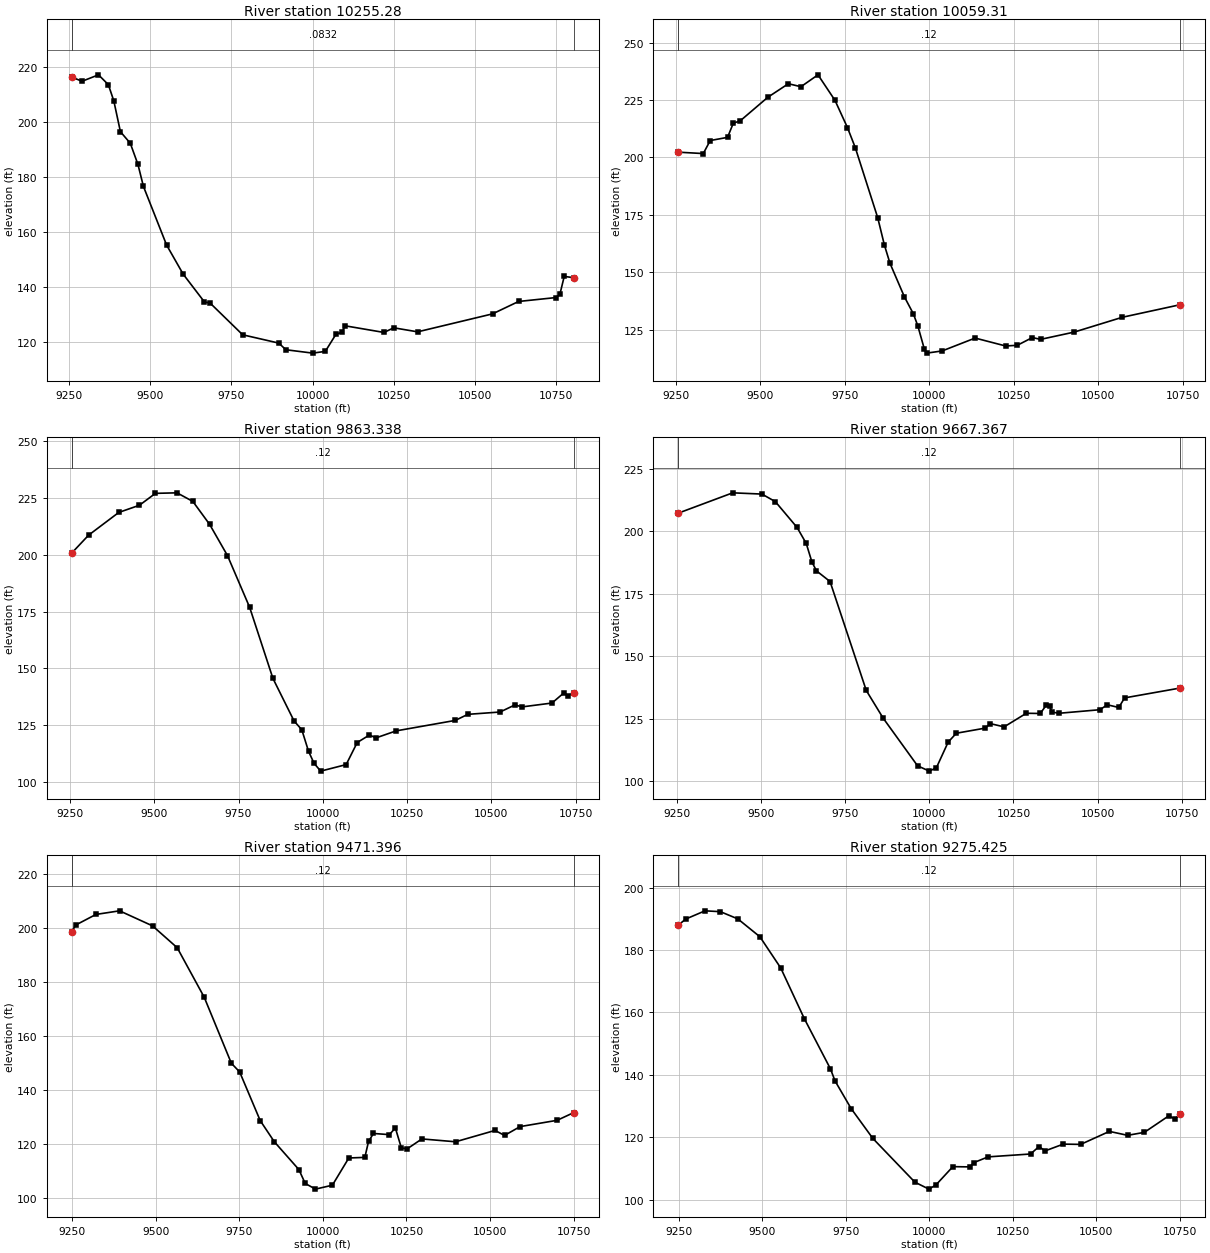
Type RM Length L Ch R = 1 ,10255.28,195.970900,195.970900,195.970900
XS GIS Cut Line= 6
1249572.39823216619168.1232471471249423.22626582 619670.29670985
1249343.24064812619769.6363548191249185.95162383619876.165063471
1249232.91054961619958.9022184311249118.86744413620540.298442423
#Sta/Elev= 30
9258.728216.21159290.359214.69599340.987  217.049371.364213.46879388.241207.5488
9408.492196.38919438.869192.19439462.496184.49849479.372176.51779550.762155.2066
9601.757144.64879667.266134.54289684.596134.15829785.005122.62329896.034119.6141
9918.125117.190810000.75115.965310039.41116.598510072.38122.844710090.38123.5073
10100.81125.881210220.09123.476110250.18125.161310323.73123.695810554.42130.2231
10634.66134.729610748.34136.131410761.71137.300210775.09143.821510804.74  143.37
#Mann= 3 , 0 , 0
9258.728  0.0832       09258.728  0.0832       010804.74  0.0832       0
#XS Ineff= 2 , 0
       09862.484        10071.72       0
Bank Sta=9258.728,10804.74
Exp/Cntr=0.3,0.1

Type RM Length L Ch R = 1 ,10059.31,195.971000,195.971000,195.971000
XS GIS Cut Line= 6
1249305.09123544618947.6054673511249229.25543184619210.931748699
1249179.73777921619433.0126294881249161.15316869619569.642097206
1249154.54083909619759.9730373281248969.86376711620387.830752382
#Sta/Elev= 30
9257.517202.30629331.559201.7007 9352.14207.37489403.377208.7658 9420.39214.9443
9440.805215.96339522.465226.23689583.288232.14389620.413230.83849670.855236.0215
9721.081224.90389757.913213.05889781.177204.27579847.535173.72759867.335161.7867
9883.834153.85259926.592139.19649952.863131.86489965.987126.65739985.672 116.346
9992.234 114.70910038.17115.6693 10135.6121.277310225.74117.828310260.31118.1194
10304.98121.503710329.04120.697910427.91123.8532 10570.9130.334610742.48135.8267
#Mann= 3 , 0 , 0
9257.517    0.12       09257.517    0.12       010742.48    0.12       0
#XS Ineff= 2 , 0
       0                 10114.6       0
Bank Sta=9257.517,10742.48
Exp/Cntr=0.3,0.1

Type RM Length L Ch R = 1 ,9863.338,195.970900,195.970900,195.970900
XS GIS Cut Line= 6
1249083.26969965618993.8152526541249016.20649814619216.504347848
1248975.39801696619428.7241623641248984.08687619 619727.06961944
1248970.66629644619935.5212388071248831.91908586620448.664350188
#Sta/Elev= 30
9255.512200.77169305.448208.6311 9394.88218.62539456.187221.7866 9503.67227.0211
9567.558227.25299614.582223.46839664.349213.37549717.323199.63399783.092176.8705
9852.036145.63049914.687126.92039937.801123.00419957.614113.57789974.031108.2863
9993.723104.826510069.26107.699110102.08117.410410138.21120.708710157.96119.4617
10217.63122.537410392.83127.1372 10430.2129.809110525.67130.8287   10570133.9694
10590.55133.072910679.64134.779410715.53139.309610727.61138.059610744.53139.3731
#Mann= 3 , 0 , 0
9255.512    0.12       09255.512    0.12       010744.53    0.12       0
#XS Ineff= 2 , 0
       0                               0
Bank Sta=9255.512,10744.53
Exp/Cntr=0.3,0.1

Type RM Length L Ch R = 1 ,9667.367,195.970900,195.970900,195.970900
XS GIS Cut Line= 6
1248992.52528208619002.9762116291248933.82215426619177.037988775
1248897.20387559619303.2034634061248805.95137115619684.869504612
1248652.05565032620132.9657464041248546.50001452620423.844056499
#Sta/Elev= 30
9254.607207.1864 9416.33215.30919503.163214.81049543.023211.78439607.546201.4666
  9634.6195.10669651.508187.69569665.035184.14129705.399179.86859812.923136.3513
9863.324125.24859965.199106.263610000.12104.128210021.12105.460310056.08115.7074
10080.32119.268410166.89121.327510180.74123.121810222.29121.812110288.09  127.24
10329.64127.160610346.95130.397810357.34130.162610364.27127.727910385.04127.2394
 10506.8128.661210528.59130.630710562.64129.564410580.09133.388110745.43137.3363
#Mann= 3 , 0 , 0
9254.607    0.12       09254.607    0.12       010745.43    0.12       0
#XS Ineff= 2 , 0
       0                               0
Bank Sta=9254.607,10745.43
Exp/Cntr=0.3,0.1

Type RM Length L Ch R = 1 ,9471.396,195.971000,195.971000,195.971000
XS GIS Cut Line= 6
1248913.03654312618944.700651343 1248706.2110078619468.956508868
1248656.20315438619571.8403527611248589.11084406619680.473460806
1248531.47857955619793.2380330591248302.42429685620314.319714025
#Sta/Elev= 30
 9249.19198.56519261.451201.0176 9321.51 204.9149392.167206.24639490.693200.6861
9564.497192.60569645.329174.28699726.439149.87819751.292146.66319812.797128.6597
9855.011120.83549928.418110.5496 9947.35105.42839978.086103.321510028.66 104.779
10077.79114.845610125.69115.058110136.75120.951410151.48123.9082   10199123.4729
10217.03125.929410235.05118.506610253.08118.282510296.35 121.88810397.02120.8328
10514.96125.026310543.55 123.18810590.01126.444910700.79128.771510750.79131.6401
#Mann= 3 , 0 , 0
 9249.19    0.12       0 9249.19    0.12       010750.79    0.12       0
#XS Ineff= 2 , 0
       0                               0
Bank Sta=9249.19,10750.79
Exp/Cntr=0.3,0.1

Type RM Length L Ch R = 1 ,9275.425,195.970900,195.970900,195.970900
XS GIS Cut Line= 6
1248793.14701511618870.6956025321248721.13999823619020.790910464
1248656.11470387 619150.769594261248507.74440368619425.111694476
1248426.63102315 619583.802301411248124.64021082620217.376131327
#Sta/Elev= 30
 9248.11187.89759270.043189.86739328.265192.52989374.269192.26119426.611189.9441
9492.644184.22449555.008174.23349625.794157.96289704.122141.85739717.616138.0433
9765.893129.16849830.939119.59749956.886105.5704    9999103.338210020.05104.6901
10070.65110.543710121.53110.465510133.29111.824910176.05113.673610303.26114.5968
 10328.7116.976410346.87115.592610401.39117.763310453.54117.6767 10539.5121.8411
10594.01120.579510644.17121.530310717.59126.838810735.76125.7845 10751.9127.3784
#Mann= 3 , 0 , 0
 9248.11    0.12       0 9248.11    0.12       0 10751.9    0.12       0
#XS Ineff= 2 , 0
       0                10099.28       0
Bank Sta=9248.11,10751.9
Exp/Cntr=0.3,0.1

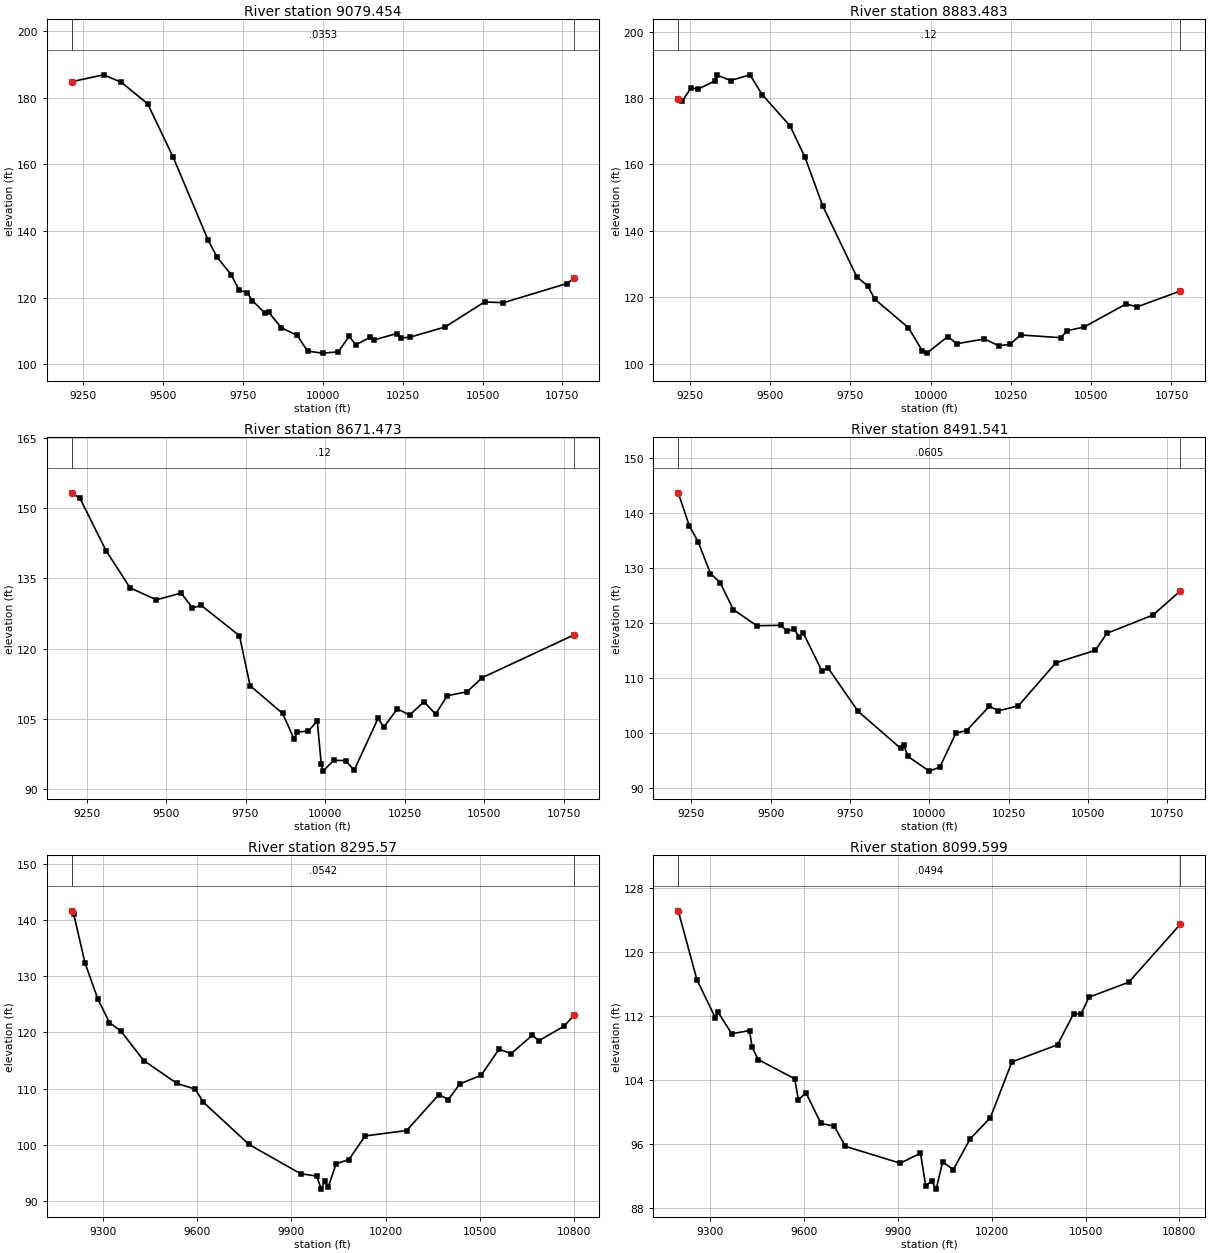
Type RM Length L Ch R = 1 ,9079.454,195.971000,195.971000,195.971000
XS GIS Cut Line= 6
1248693.88950648 618815.58798145  1248588.587669619012.351261721
1248503.35891503619154.1374388871248274.45861977619455.997470525
1248109.77799648619739.4329757061247892.24881244620163.144282449
#Sta/Elev= 30
9214.094184.78569313.911186.83999369.728184.57799451.874 178.1169531.631 162.106
9641.252137.19099669.251132.15299713.438126.83989738.034122.25119762.981121.5473
9779.612119.11149817.922115.43659830.706115.59229870.473 110.9679920.068108.6645
9952.256103.95089999.111103.364310048.07 103.73310082.56108.396810103.23105.8575
10147.71108.0838 10159.2107.291910231.65109.242210244.68107.878610272.99 108.152
10382.51111.1991 10506.6118.710110565.48118.492110764.22124.240510785.97125.7757
#Mann= 3 , 0 , 0
9214.094  0.0353       09214.094  0.0353       010785.97  0.0353       0
#XS Ineff= 2 , 0
       0                10065.08       0
Bank Sta=9214.094,10785.97
Exp/Cntr=0.3,0.1

Type RM Length L Ch R = 1 ,8883.483,212.009800,212.009800,212.009800
XS GIS Cut Line= 6
1248649.25103512618694.8101682961248385.38111019619139.751348197
1248272.17637038619258.4283273071248152.26636747 619313.72416836
1248047.58726919619454.7744243291247810.72594008 619976.79133302
#Sta/Elev= 30
9213.599179.79649225.664179.02729253.436183.00099275.905182.68169327.727185.1253
9335.824186.83989377.019185.25599437.076186.97059474.962181.0268  9562.1171.5585
9608.674162.10429663.196147.59549770.083126.10759803.687123.39949826.112119.3752
9930.622110.83049974.326103.77889988.267103.160410053.15108.138310081.75106.0026
10167.55107.419910211.52105.390510247.08105.799710279.98108.627910406.07107.8017
10424.09109.901910477.34111.001610607.83117.921710643.86117.116210777.56 121.864
#Mann= 3 , 0 , 0
9213.599    0.12       09213.599    0.12       010777.56    0.12       0
#XS Ineff= 2 , 0
       0                10045.93       0
Bank Sta=9213.599,10777.56
Exp/Cntr=0.3,0.1

Type RM Length L Ch R = 1 ,8671.473,179.932000,179.932000,179.932000
XS GIS Cut Line= 6
1248211.75610419618511.0431807681247989.83307931 618978.92450886
1247972.87195902619141.8473167851248029.62572292619282.155626082
1248020.60924006 619371.082755361247736.53109314619954.510378554
#Sta/Elev= 30
9203.564153.26979229.565152.0797 9311.31140.92469386.827132.97239469.792130.4176
9547.463131.84979582.909128.70359610.999129.20189730.909122.73849764.407112.0681
9866.731106.13439902.973100.61179912.915102.19189946.705102.32239975.641104.5116
9988.16895.297169993.237 93.811810028.01 96.135710064.8196.0460710091.7794.01111
10166.96105.115210184.65103.206310227.66107.123710265.75 105.78310311.32108.6345
10347.69105.979210384.29109.921410446.51110.757410494.09113.774610782.45122.9017
#Mann= 3 , 0 , 0
9203.564    0.12       09203.564    0.12       010782.45    0.12       0
#XS Ineff= 2 , 0
       0                10041.12       0
Bank Sta=9203.564,10782.45
Exp/Cntr=0.3,0.1

Type RM Length L Ch R = 1 ,8491.541,195.971000,195.971000,195.971000
XS GIS Cut Line= 6
1248106.28192934618516.7697781371247998.49967429618692.809459976
1247923.64637506618861.9626122111247816.35369566619342.661534149
1247759.84750777 619514.842622041247527.55369236619976.129847997
#Sta/Elev= 30
9208.551 143.6339243.624137.60439271.197 134.7539310.088128.96199340.733127.2965
9382.295122.39669456.029 119.4689531.993119.54189552.294118.4527 9574.36118.8776
9588.483117.44159602.544118.19569661.044111.29649681.691 111.7249775.659103.8915
9909.89497.168959919.87197.688899933.17395.686969999.79993.0265310033.4193.76422
10083.8399.91093 10117.8100.413610189.78 104.84110217.72103.991510280.71 104.887
10398.97112.715410523.28114.992110560.31118.097410705.49121.412210791.46125.7988
#Mann= 3 , 0 , 0
9208.551  0.0605       09208.551  0.0605       010791.46  0.0605       0
#XS Ineff= 2 , 0
       0                               0
Bank Sta=9208.551,10791.46
Exp/Cntr=0.3,0.1

Type RM Length L Ch R = 1 , 8295.57,195.970900,195.970900,195.970900
XS GIS Cut Line= 6
1248033.53186518 618469.594647341247928.47746978618614.945850784
1247850.69446152 618747.775675451247699.34594593619097.820936197
1247521.57547038619453.2799826431247277.40242709619874.128370509
#Sta/Elev= 30
9200.486141.70339206.519141.14299242.625132.41589283.602125.94449320.397121.7707
9356.914120.25579429.769114.99959535.639110.89939593.802109.90929619.248107.5758
9765.198100.01829929.23894.806239980.447 94.38889995.07992.0556610006.2693.44263
10017.2792.3991710042.1196.5705710083.3197.3287310134.68101.547410266.77102.5065
10370.11108.936610399.77108.042810436.87110.837810504.72112.369710561.32117.0403
10599.55116.219310667.82119.529610687.89118.525610769.26121.154510799.56123.0511
#Mann= 3 , 0 , 0
9200.486  0.0542       09200.486  0.0542       010799.56  0.0542       0
#XS Ineff= 2 , 0
       0                               0
Bank Sta=9200.486,10799.56
Exp/Cntr=0.3,0.1

Type RM Length L Ch R = 1 ,8099.599,145.224000,145.224000,145.224000
XS GIS Cut Line= 6
1247908.02788002618429.9378939211247705.48243749618676.680768783
1247573.78373117618871.3436840821247514.87713758618989.589654717
1247402.74808512619310.1398881051247098.58627455619802.342002224
#Sta/Elev= 30
9196.807125.09579256.486116.5189 9315.15111.77699323.798112.48949367.912109.7686
9425.041110.16029433.382108.05169452.937106.54149569.234104.15259581.341101.5278
9605.555102.40019653.29298.583069696.05998.251259731.12195.733329906.93593.62104
9971.90694.865839988.70390.7920110007.41 91.4014 10022.290.3876610042.6593.77513
10077.2292.8285410130.1896.6216610195.5499.30704 10264.4106.250210410.35108.3902
 10461.6112.242810485.83112.2554 10511.1114.328710638.54116.196710803.26123.4208
#Mann= 3 , 0 , 0
9196.807  0.0494       09196.807  0.0494       010803.26  0.0494       0
#XS Ineff= 2 , 0
       0                               0
Bank Sta=9196.807,10803.26
Exp/Cntr=0.3,0.1

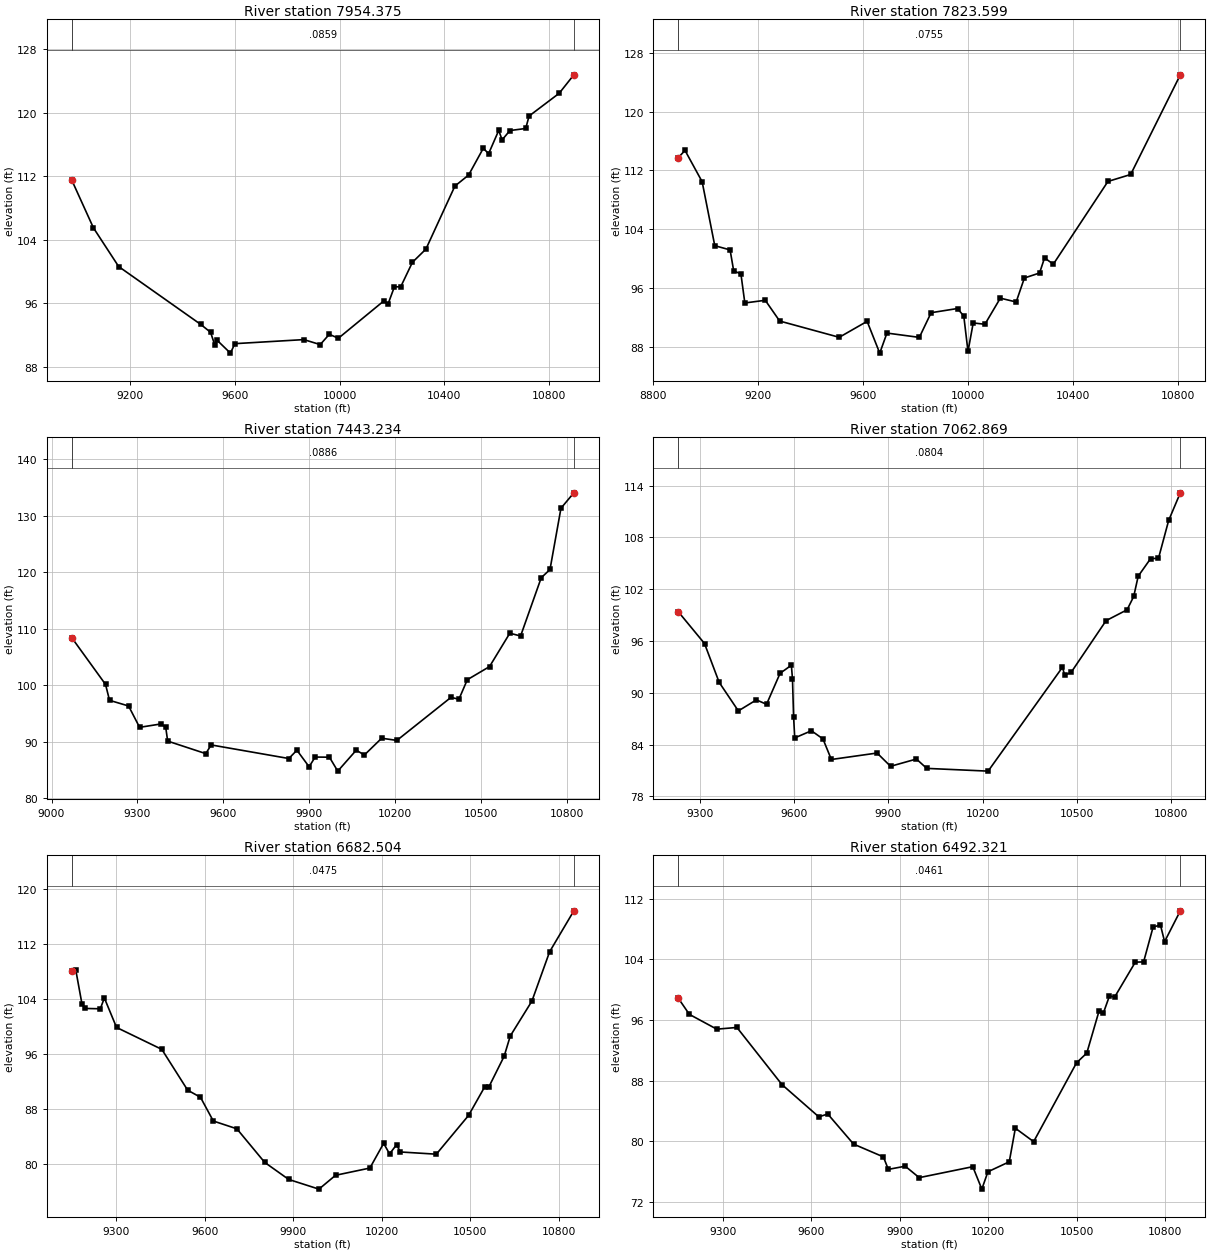
Type RM Length L Ch R = 1 ,7954.375,130.776000,130.776000,130.776000
XS GIS Cut Line= 5
1247663.91911092618083.2756221291247461.65029266618720.149063438
1247319.51544738619132.8867871761247212.91431344619471.823725909
1246917.71117324619821.694114253
#Sta/Elev= 30
8976.441111.49649059.173105.47929155.558100.60659468.80993.317659506.675 92.3197
 9523.1890.660429530.77191.340769582.40689.693469599.61790.88711 9862.9791.39762
9925.42990.768759960.12892.064199994.82891.5686810167.5596.2480310184.7395.89651
10208.8398.05121 10232.998.0475610277.61101.1378 10329.2102.802510439.94110.7464
10492.34112.1375 10548.3 115.50410568.72114.828910607.36117.760410620.23 116.567
10650.05117.741510710.38118.004410723.26 119.573 10838.3122.438410894.27124.7651
#Mann= 3 , 0 , 0
8976.441  0.0859       08976.441  0.0859       010894.27  0.0859       0
#XS Ineff= 2 , 0
       09631.073                       0
Bank Sta=8976.441,10894.27
Exp/Cntr=0.3,0.1

Type RM Length L Ch R = 1 ,7823.599,380.365100,380.365100,380.365100
XS GIS Cut Line= 6
1247617.45194998 617927.473964811247300.29546607 618933.88287051
1247191.41680625619011.5479433091247076.79670179619109.977116361
1246910.31746429 619272.154823841246672.94099852619520.114488959
#Sta/Elev= 30
8894.765113.7375 8920.64 114.7238985.998110.46539034.157101.76559092.635101.1911
9106.39498.330139133.91397.933579148.88193.97332 9226.79 94.34019281.82991.51535
9509.09489.303549615.49891.473779663.65687.151169691.17589.880039814.72989.29154
 9859.7392.650179960.39693.21946 9984.3792.1881410000.3887.3836610020.3191.25851
10064.9991.0761910123.7494.6283910184.2494.1084110215.5897.3702110273.4698.05032
10292.54100.108910325.9499.2454710534.36110.503910621.11111.449210810.54125.0062
#Mann= 3 , 0 , 0
8894.765  0.0755       08894.765  0.0755       010810.54  0.0755       0
#XS Ineff= 2 , 0
       09660.729        10040.32       0
Bank Sta=8894.765,10810.54
Exp/Cntr=0.3,0.1

Type RM Length L Ch R = 1 ,7443.234,380.365100,380.365100,380.365100
XS GIS Cut Line= 6
1247573.93612251617907.3193193081247344.23618749618521.368731081
1247125.93087858618610.4746346771246751.01672152618774.797757909
1246574.19139528618865.1852441881246354.23996696 618993.95944427
#Sta/Elev= 30
9070.776108.40969188.701100.15859202.71397.343079269.26796.343699307.79892.56792
9381.35993.158499398.87392.632619405.87990.137789538.98887.921559557.86489.45877
 9829.1687.057349857.50988.523159900.03285.602579921.29487.316059971.11287.29101
10000.1784.8284410064.7988.53168 10093.287.6793210153.5890.6424510206.8590.25874
10395.6597.8596910423.5997.54119 10452.9100.986510530.48103.305610601.43109.2076
10639.05108.712910711.14119.006110741.79120.468210780.11   131.310825.12 134.019
#Mann= 3 , 0 , 0
9070.776  0.0886       09070.776  0.0886       010825.12  0.0886       0
#XS Ineff= 2 , 0
       09806.937        10060.72       0
Bank Sta=9070.776,10825.12
Exp/Cntr=0.3,0.1

Type RM Length L Ch R = 1 ,7062.869,380.365100,380.365100,380.365100
XS GIS Cut Line= 6
1247503.80186054617852.7704488781247340.32327598618222.424588159
1247149.15590739618252.526313141 1246735.2951749618295.313468128
 1246424.6319834618382.612871677 1246184.9299871618482.426600024
#Sta/Elev= 30
9231.96599.39211 9315.5295.705629362.15691.203639423.14187.896499480.53989.17425
9512.82588.662059555.87392.252879591.74793.186029595.33491.617689598.92187.15578
9602.509 84.76769655.54185.596879692.23784.651389718.92582.267629864.45883.01596
9907.272 81.4771 9989.5282.3214410022.3781.2368210217.5580.9186110454.1192.95869
10460.9492.0391310481.5492.3583610592.7198.3514210659.5299.6124810680.61 101.152
 10694.9 103.50810734.37105.540610759.45105.575410791.73109.958610828.85113.1638
#Mann= 3 , 0 , 0
9231.965  0.0804       09231.965  0.0804       010828.85  0.0804       0
#XS Ineff= 2 , 0
       09756.235         10111.7       0
Bank Sta=9231.965,10828.85
Exp/Cntr=0.3,0.1

Type RM Length L Ch R = 1 ,6682.504,190.182500,190.182500,190.182500
XS GIS Cut Line= 6
 1247799.7588645617705.6173850881247602.58254938617770.815611247
1247404.91354648617819.7029415571246646.59658597617946.665461397
1246419.67971186618011.8032045941246152.77658012618113.476891373
#Sta/Elev= 30
9148.792108.18839162.205108.31329183.124103.37969193.583102.67069245.556102.6211
9259.316104.19189300.597 99.90569454.08296.713459541.65990.776649585.23389.73288
9628.69786.280929708.56585.14659 9802.9380.25804 9884.2677.775549986.91276.36345
10043.2578.38004 10159.679.4323410206.3283.0308710226.35 81.493810249.8982.81694
10263.3481.7725810384.8981.4512110494.1387.0872210549.0291.2611210562.7591.21922
10614.82 95.704210635.67 98.663610708.96103.7381   10769110.9181 10851.2116.8838
#Mann= 3 , 0 , 0
9148.792  0.0475       09148.792  0.0475       0 10851.2  0.0475       0
#XS Ineff= 2 , 0
       0                               0
Bank Sta=9148.792,10851.2
Exp/Cntr=0.3,0.1

Type RM Length L Ch R = 1 ,6492.321,190.182600,190.182600,190.182600
XS GIS Cut Line= 6
  1247760.811563617485.5745639151247498.20728633617564.091635511
1247007.49316148617680.7760890621246802.35147054617740.167409385
1246405.85933463617870.9218236481246133.70219767617978.742368366
#Sta/Elev= 30
9148.78798.876839186.54896.735819279.43694.784379347.77395.00858 9500.4587.47445
9625.45783.217669655.76783.592159743.32979.623039844.362 77.93599861.20176.28783
9918.45376.707619965.93875.1970210147.5376.6433110178.2373.6831310198.8975.97366
10271.2177.2882310291.8781.7191310353.8679.9442110499.4490.3517510534.1191.63081
10575.91 97.213510589.9496.8697310610.9899.1690410628.5199.0152210698.65103.6269
10726.73103.655810758.77108.230610783.69108.548910797.93106.332510851.21110.3942
#Mann= 3 , 0 , 0
9148.787  0.0461       09148.787  0.0461       010851.21  0.0461       0
#XS Ineff= 2 , 0
       0                               0
Bank Sta=9148.787,10851.21
Exp/Cntr=0.3,0.1

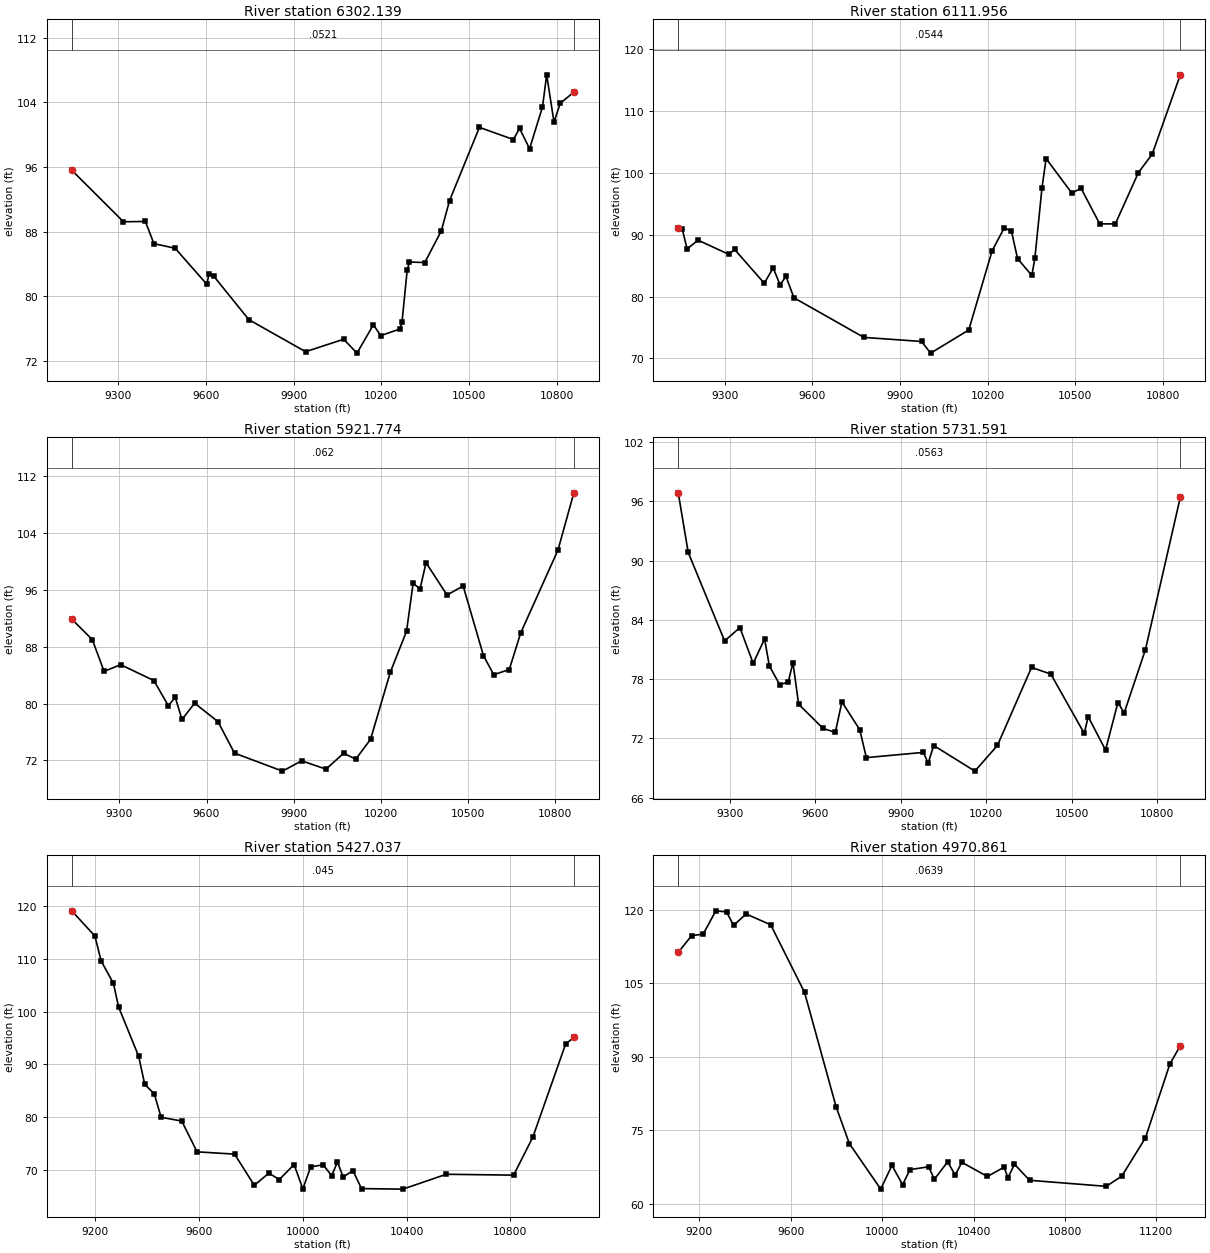
Type RM Length L Ch R = 1 ,6302.139,190.182500,190.182500,190.182500
XS GIS Cut Line= 6
1247707.45576993617274.980326388 1247155.1816568617428.631395417
1246863.45781807617523.956211197 1246643.4488854 617636.87515067
1246247.88097234617792.9651602271246097.62635994617858.362781415
#Sta/Elev= 30
9141.53295.615539318.32989.226359393.09489.263629422.55486.519899494.94685.94671
9603.66381.470849610.47882.726489627.51582.468829747.09777.101849941.10373.13563
10071.2674.6757510116.8372.9573210172.8676.46433 10198.375.12369 10263.575.94825
10270.7176.7591910288.4483.22081 10296.1 84.2338 10348.784.1818910405.2588.10358
10433.4191.8562310535.52100.918410651.7199.4146310672.84 100.78810707.04 98.2705
 10751.2103.452910765.51107.426410790.56101.567410812.03103.911710858.41105.2765
#Mann= 3 , 0 , 0
9141.532  0.0521       09141.532  0.0521       010858.41  0.0521       0
#XS Ineff= 2 , 0
       0                               0
Bank Sta=9141.532,10858.41
Exp/Cntr=0.3,0.1

Type RM Length L Ch R = 1 ,6111.956,190.182500,190.182500,190.182500
XS GIS Cut Line= 6
1247596.69101547617150.4859334331247097.24211047617279.781939254
1246848.13476588617366.373225853 1246630.3952226617429.772981015
1246246.21345947617572.1092039791245972.09079741617699.000914596
#Sta/Elev= 30
9140.65991.132889154.07390.970419171.04387.699769208.37989.117799313.66386.83517
 9333.7487.612529435.15982.153589465.58584.648459489.24981.903399509.53383.26278
9536.65179.812419776.28673.404969973.718 72.750410004.6870.8654410135.1374.60234
10215.1387.4024110256.74 91.112210281.3490.5676510302.2586.1353110351.0383.41482
10361.48 86.175910385.9297.61838   10400102.299810487.9696.7261610519.63 97.5138
10583.3291.7582710636.8491.7416610715.85100.028810763.14103.027310859.36115.8381
#Mann= 3 , 0 , 0
9140.659  0.0544       09140.659  0.0544       010859.36  0.0544       0
#XS Ineff= 2 , 0
       0                               0
Bank Sta=9140.659,10859.36
Exp/Cntr=0.3,0.1

Type RM Length L Ch R = 1 ,5921.774,190.182600,190.182600,190.182600
XS GIS Cut Line= 6
1247583.27402588617002.1138781211246853.77044694617162.485950325
1246674.05557001617241.1606201541246384.27745535617323.506220039
1246218.02619414617381.2417766831245940.86837625617511.754581289
#Sta/Elev= 30
9136.26491.879239206.87289.009639247.39384.532239304.56885.472639418.55183.24245
9468.72979.690079492.14580.893989515.56277.763819559.04980.053599639.33477.45445
9696.202 73.02619861.28670.494289927.22471.9452810010.8970.7734210071.8573.01405
10113.2972.1705210164.4274.98079 10232.484.4283110288.1290.1782110310.7296.90464
10334.6696.1458210355.1899.8242410427.4195.2698810482.8996.5534110552.7486.74788
10588.2384.0581710641.5884.7923910680.8389.9328210809.12101.599610863.74109.6534
#Mann= 3 , 0 , 0
9136.264   0.062       09136.264   0.062       010863.74   0.062       0
#XS Ineff= 2 , 0
       0                               0
Bank Sta=9136.264,10863.74
Exp/Cntr=0.3,0.1

Type RM Length L Ch R = 1 ,5731.591,304.554600,304.554600,304.554600
XS GIS Cut Line= 6
1247581.59127646616909.7291696031247095.27911304 617000.12934506
1246541.54257823617030.2851450071246351.78956492 617058.01855202
1246089.51119751617147.1002227121245878.69217006617267.547108941
#Sta/Elev= 30
9118.71496.857579153.63790.82859 9281.58 81.85939335.13383.218539381.856 79.5901
9421.76282.06327 9438.39 79.34749474.97177.429849504.88477.703029521.43579.66726
9541.29675.457089627.31772.996689670.21772.605699693.31675.695519756.00672.86572
9779.04170.046439979.51870.577329995.92369.4721910015.6171.2706810160.0768.67891
10239.2771.2799410359.0379.1821110426.6578.5034110544.0972.4961210557.74 74.1955
10618.7370.8175110662.2575.6210510684.2274.5742810758.7780.9840510881.2496.41123
#Mann= 3 , 0 , 0
9118.714  0.0563       09118.714  0.0563       010881.24  0.0563       0
#XS Ineff= 2 , 0
       0                10196.77       0
Bank Sta=9118.714,10881.24
Exp/Cntr=0.3,0.1

Type RM Length L Ch R = 1 ,5427.037,456.175600,456.175600,456.175600
XS GIS Cut Line= 6
1247616.77825469616675.4323773531247342.56535503616743.878008112
1247104.85596097616768.6232315451246908.81098017616757.756456003
1246669.67162493616709.222983837 1245810.1893121617161.818090156
#Sta/Elev= 30
9110.334119.14039199.473114.35089223.371109.63159270.719105.38659290.937 100.856
9367.99491.528729391.44686.20075 9428.0384.390649454.55479.946499533.85879.23986
9593.02173.39669 9737.4972.959329813.31767.043019869.75569.351479909.69968.13407
9966.78770.9832510000.3966.3475410030.6170.5499410078.8970.9284310111.4868.86424
10133.7371.4574710155.9868.6045610193.06 69.841310226.4366.4158210385.87 66.3172
10552.72 69.136310812.2868.9732210886.4476.2013211012.5193.83916 11044.395.10741
#Mann= 3 , 0 , 0
9110.334   0.045       09110.334   0.045       0 11044.3   0.045       0
#XS Ineff= 2 , 0
       0                10066.45       0
Bank Sta=9110.334,11044.3
Exp/Cntr=0.3,0.1

Type RM Length L Ch R = 1 ,4970.861,380.365100,380.365100,380.365100
XS GIS Cut Line= 6
1247601.87791431615842.4885670541247106.82321674616152.376348123
1246923.23317453616244.9685172741246807.17206863616281.873727664
1246446.59280041616553.987819701 1245810.1893121 617091.68382819
#Sta/Elev= 30
9107.915 111.342 9166.73114.76299216.888115.0519 9272.31119.81749319.145119.5909
9350.346116.85319404.892119.17339512.547116.96719660.591103.17779798.46479.86917
9856.75672.320079993.97563.0349410043.0367.8863410089.7163.9491410121.9867.01298
10203.6967.5937810228.5965.0348110286.6768.6018410319.8665.90385 10348.968.49831
10460.9265.6160810533.5367.5047910550.7465.3573110579.2868.1146910645.37 64.8362
10980.8863.6022311048.9765.7020311152.0573.4668211259.4388.5994211304.8592.28784
#Mann= 3 , 0 , 0
9107.915  0.0639       09107.915  0.0639       011304.85  0.0639       0
#XS Ineff= 2 , 0
       0                10237.28       0
Bank Sta=9107.915,11304.85
Exp/Cntr=0.3,0.1

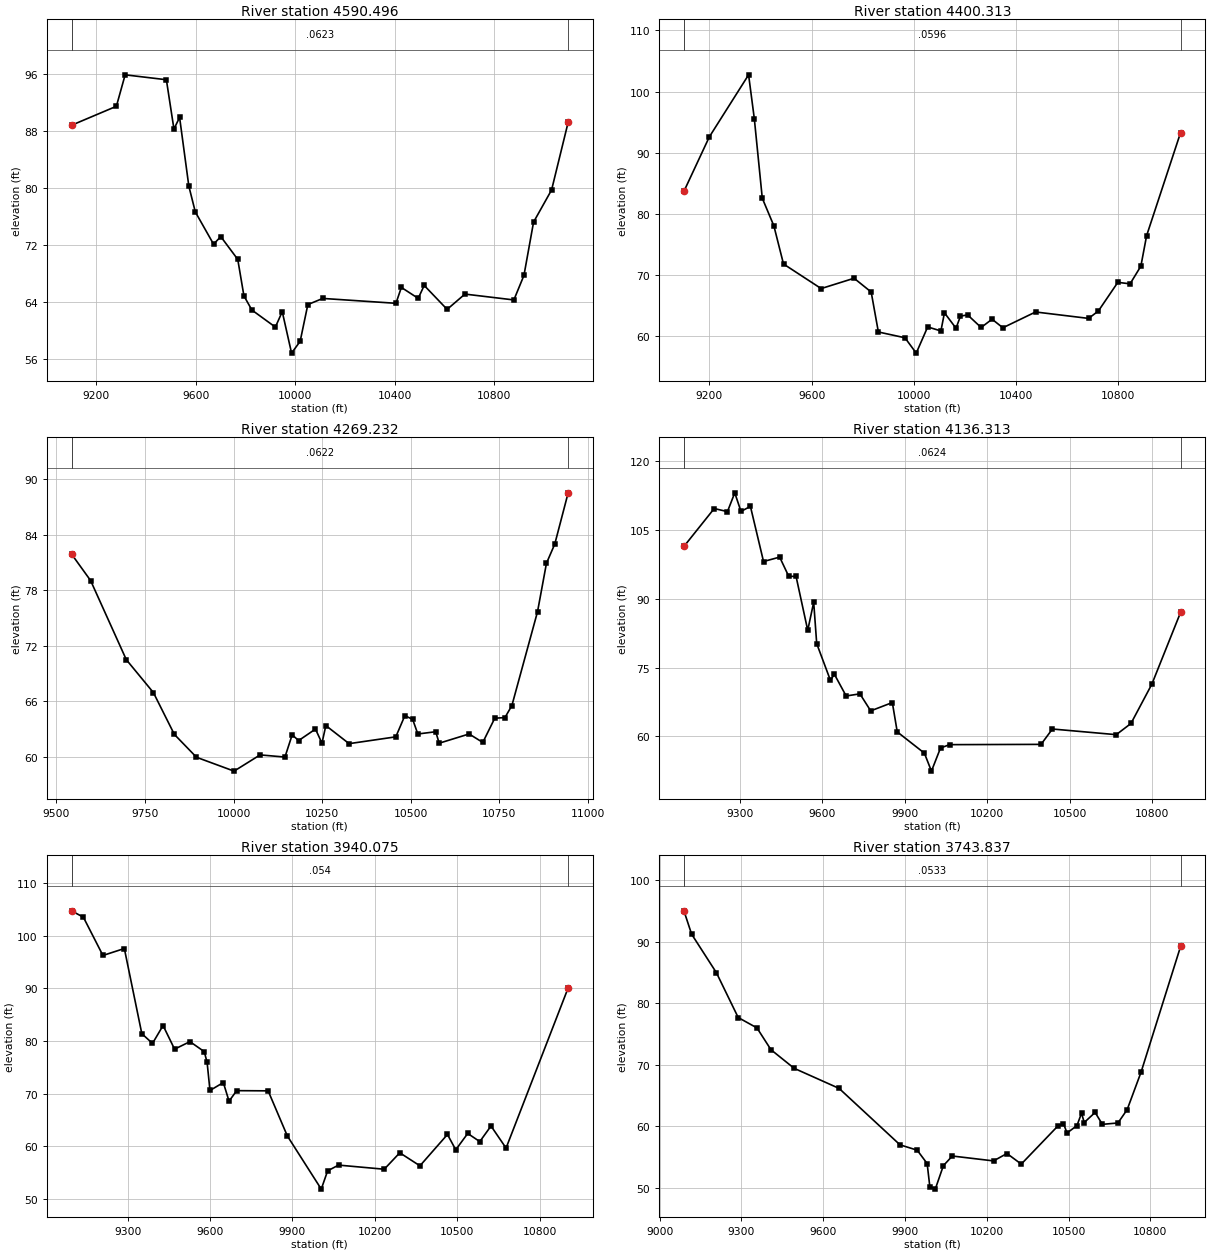
Type RM Length L Ch R = 1 ,4590.496,190.182500,190.182500,190.182500
XS GIS Cut Line= 6
1246898.53091654615355.7991423761246617.91878143615808.241295114
 1246529.2044971 616010.286013291246466.28503722 616205.98622714
1246343.57601511616429.8460910021245812.78687733617003.366609409
#Sta/Elev= 30
9101.06288.835939281.47191.504699316.62795.925089482.355  95.2359512.76188.30425
9535.48789.943569572.60280.281069598.58376.660239671.95872.124979700.99673.18723
9769.19769.987629794.01764.860219825.92862.869979920.36360.468989948.05962.63731
9985.44656.8112610019.9958.4696910050.8463.6347910110.8664.4989410405.0263.81397
10426.7266.0449710494.4364.5079710518.4966.3254510610.6562.9588510682.1865.10906
10878.8764.28691 10919.467.7397310958.0475.2282411030.4979.7473711097.0689.26052
#Mann= 3 , 0 , 0
9101.062  0.0623       09101.062  0.0623       011097.06  0.0623       0
#XS Ineff= 2 , 0
       0                10196.33       0
Bank Sta=9101.062,11097.06
Exp/Cntr=0.3,0.1

Type RM Length L Ch R = 1 ,4400.313,131.081200,131.081200,131.081200
XS GIS Cut Line= 6
1246714.28450039 615290.669909851246557.34672511615516.934240073
1246437.65445045 615738.731897191246159.72278419616457.784058109
1245985.54352391616711.3901733611245755.64044166616956.610434756
#Sta/Elev= 30
9100.40583.700739199.77592.591289353.497102.73029375.91495.574789407.08482.57778
9452.387 78.07129490.14171.835559637.56267.821799766.35469.507159833.276 67.2603
9861.44260.731829965.44259.7868710009.6457.2788710054.4261.56032 10106.260.89883
10120.0363.86438 10165.361.3454210182.7163.3190910210.5663.5262810263.5861.46669
10306.4562.8200110348.6861.4189110476.7163.9993910684.1562.9497510722.4164.15544
10798.6168.8396810846.5868.59635 10888.871.4862910911.2976.4663711044.2293.29395
#Mann= 3 , 0 , 0
9100.405  0.0596       09100.405  0.0596       011044.22  0.0596       0
#XS Ineff= 2 , 0
       0                10202.62       0
Bank Sta=9100.405,11044.22
Exp/Cntr=0.3,0.1

Type RM Length L Ch R = 1 ,4269.232,132.918800,132.918800,132.918800
XS GIS Cut Line= 5
1246323.57280195615621.0943028931246185.69569424616014.383101821
1246147.27092654616213.2877817151245986.79101431616538.768167049
1245758.50268853616891.371917799
#Sta/Elev= 30
9542.51781.926479596.43379.056729697.254 70.49379773.73966.934239832.84262.41348
9895.42159.9344210001.4958.43507   1007560.1910410145.1759.9573710165.5462.36084
10183.8361.7431610231.3862.9850810249.6761.4567810260.6563.3656810326.3261.40737
10458.1862.1447810483.7864.4424810505.7364.0353210520.3662.4536610570.8762.69757
10580.6161.4560110665.1362.4562610703.7661.5394210737.5764.1607810766.2964.23022
10785.8665.52485 10858.375.6840910883.5480.92813   1090783.00282 10944.888.54749
#Mann= 3 , 0 , 0
9542.517  0.0622       09542.517  0.0622       0 10944.8  0.0622       0
#XS Ineff= 2 , 0
       0                10197.88       0
Bank Sta=9542.517,10944.8
Exp/Cntr=0.3,0.1

Type RM Length L Ch R = 1 ,4136.313,196.238300,196.238300,196.238300
XS GIS Cut Line= 6
1246459.51461691615200.5686025881246301.66826998615466.369089943
1246025.25587885616065.398264864 1245858.1921684616556.678465809
1245778.73580968616732.9780308611245718.82444042616841.756962725
#Sta/Elev= 30
 9096.96101.33449207.158109.58279255.236108.91029281.857112.99839304.431108.9508
9338.778110.05189386.43898.057019445.11699.016359478.25294.817219504.687 94.8363
 9547.1883.090249568.85989.194569579.83580.197299629.72672.210569644.01873.54034
9686.89668.808069736.92169.271579776.22665.570059854.83667.379879872.70260.99816
9971.33256.375799997.08552.46179   1003057.4858310062.9158.2217810395.6358.28081
10436.8961.6231810669.0660.3919210722.6162.8270210798.6171.3822610903.0486.99743
#Mann= 3 , 0 , 0
 9096.96  0.0624       0 9096.96  0.0624       010903.04  0.0624       0
#XS Ineff= 2 , 0
       0                10236.33       0
Bank Sta=9096.96,10903.04
Exp/Cntr=0.3,0.1

Type RM Length L Ch R = 1 ,3940.075,196.238300,196.238300,196.238300
XS GIS Cut Line= 6
1246203.67851649615094.9964395391246086.40129597615374.934783615
1245909.25237607615873.4383189481245837.35089949616014.981290651
1245735.18910886616501.6137200431245627.23980225616801.042604743
#Sta/Elev= 30
9095.887104.7007 9139.14103.49039210.31396.227329288.26497.547649351.87681.38773
 9390.7579.53289 9429.27 82.9289 9471.1878.441629527.06179.873989579.18577.97776
  9589.675.924759600.01670.601729648.623 72.10859669.45568.57008 9697.2370.56996
9811.804 70.53169881.62261.9779810005.1951.8775310028.3655.3485110068.1256.43869
 10234.455.6541510291.0958.7746410364.44 56.301610464.6262.25134 10494.8 59.3482
10538.44 62.441410582.36 60.901210623.1963.8596210678.01 59.669210904.0790.07715
#Mann= 3 , 0 , 0
9095.887   0.054       09095.887   0.054       010904.07   0.054       0
#XS Ineff= 2 , 0
       0                10300.93       0
Bank Sta=9095.887,10904.07
Exp/Cntr=0.3,0.1

Type RM Length L Ch R = 1 ,3743.837,196.238300,196.238300,196.238300
XS GIS Cut Line= 6
1245910.56775768614999.5237755921245812.68377239615279.629720781
1245734.14038555615608.4320396841245686.08876263615915.006309353
1245675.89690233616386.5179174681245575.16701024616776.552114942
#Sta/Elev= 30
9089.12295.039079117.30391.245789208.31684.970379288.23977.684529357.02675.99729
 9408.3872.452319493.41769.426079658.30766.158779881.66456.982729944.72756.11169
9981.23753.940999991.19450.1406710011.0849.7781210040.79  53.599 10073.655.16268
10224.7254.3677910273.9455.5708810326.4853.8491310461.4360.0780710481.2160.44949
 10494.458.9042610530.8560.1185610547.4662.1347410557.4360.61398 10597.362.25003
10624.0160.3137410681.1260.5391410714.9262.7142410766.0468.8237410910.8389.24316
#Mann= 3 , 0 , 0
9089.122  0.0533       09089.122  0.0533       010910.83  0.0533       0
#XS Ineff= 2 , 0
       0                10341.38       0
Bank Sta=9089.122,10910.83
Exp/Cntr=0.3,0.1

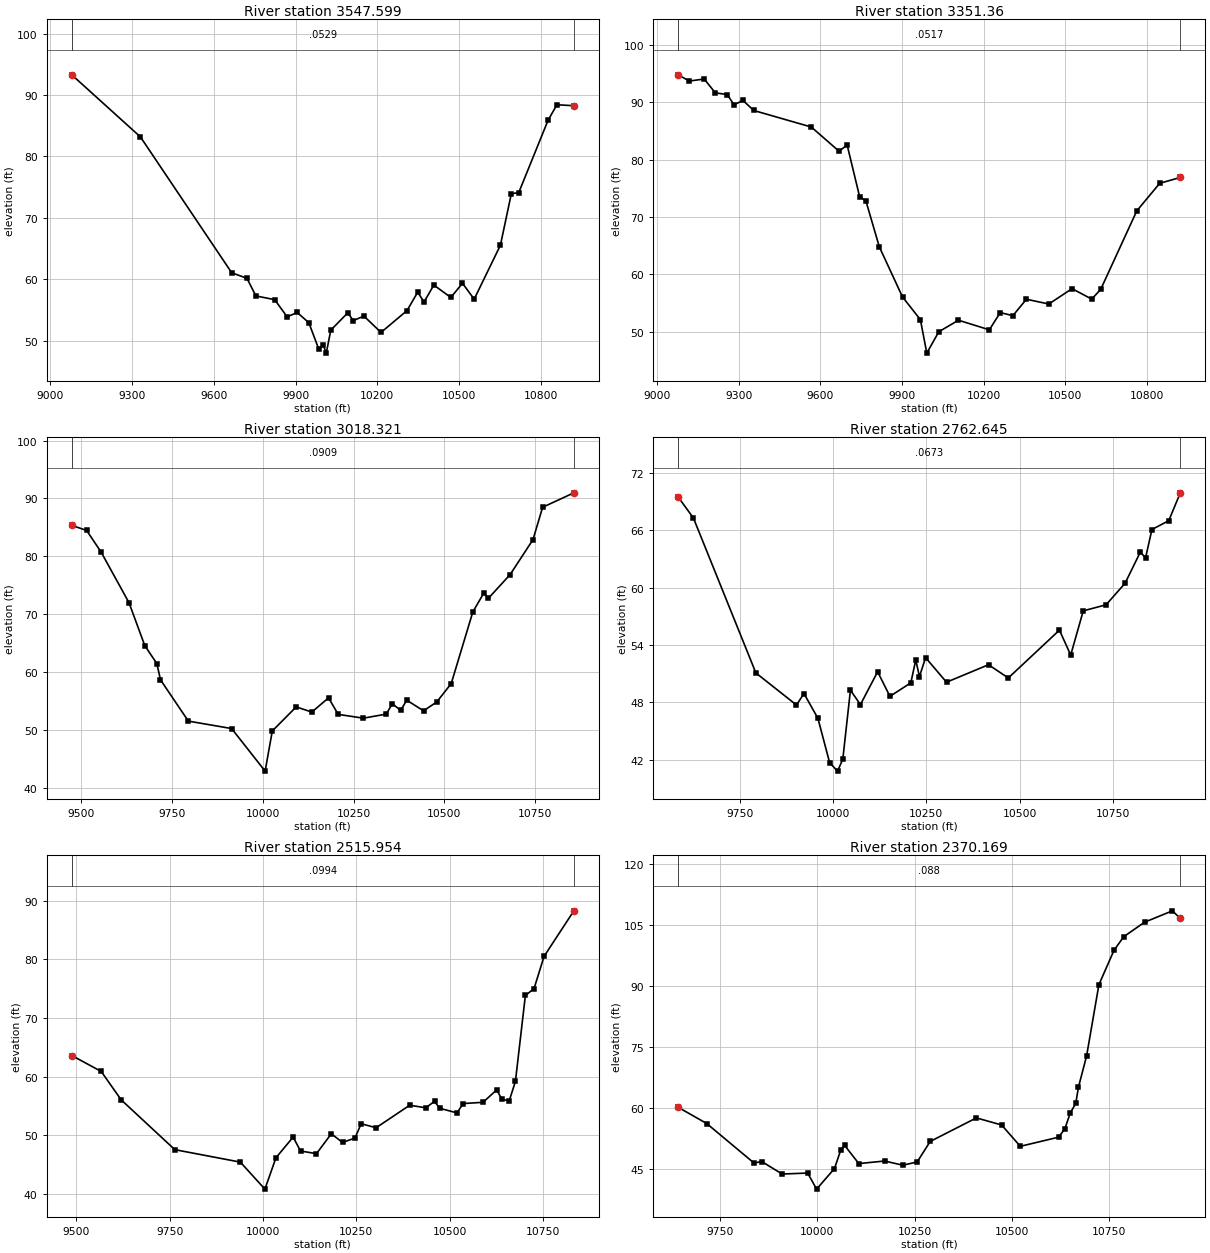
Type RM Length L Ch R = 1 ,3547.599,196.238400,196.238400,196.238400
XS GIS Cut Line= 6
1245638.28389445615035.1404919391245532.82068441615528.506749459
1245516.74419898616005.6130307721245532.56230227616412.102998229
1245503.05266161616627.642603453 1245436.1662785616849.297398121
#Sta/Elev= 30
9078.84793.283779330.81683.181939665.69461.086459721.62960.179999754.45257.31535
9823.38656.708059869.35553.903469905.71354.632229948.726 52.96159984.99448.68338
10002.2949.2578410012.6348.0098710029.3851.7481110091.8354.5698310111.5353.30781
10151.0354.0319110213.5951.3779610308.9554.9273910348.3457.9284110371.3156.31191
10407.4159.0839710469.7857.0681410512.6159.3754710555.4556.7878310651.7465.56469
10691.8673.9578110718.8674.1079510826.6185.8926510859.0688.41362 10921.288.26068
#Mann= 3 , 0 , 0
9078.847  0.0529       09078.847  0.0529       0 10921.2  0.0529       0
#XS Ineff= 2 , 0
       0                10314.02       0
Bank Sta=9078.847,10921.2
Exp/Cntr=0.3,0.1

Type RM Length L Ch R = 1 , 3351.36,333.038700,333.038700,333.038700
XS GIS Cut Line= 6
1245450.51921704614980.5287394261245383.77715734615235.022903336
 1245352.0565622615506.9673075171245343.14800143615855.229773772
1245408.35778638616412.9495950671245344.47963102616801.261407839
#Sta/Elev= 30
9077.878 94.81779118.52393.730429173.25294.087719214.11391.67087 9257.9891.37855
9282.728 89.58369315.72590.34974 9355.1488.595939566.774  85.7059668.67481.47478
9698.22582.58425 9744.1773.53337 9767.1472.821349816.36464.805399901.68456.04898
9967.35352.083059990.87746.2421310034.9349.9707210107.2151.9875410220.5750.30959
10260.6553.31494 10307.152.7808810356.8455.6480210439.1154.8146410524.45 57.4986
10596.7355.6654510629.62 57.365810762.3171.0814710846.3775.8801910922.0776.90368
#Mann= 3 , 0 , 0
9077.878  0.0517       09077.878  0.0517       010922.07  0.0517       0
#XS Ineff= 2 , 0
       0                10389.42       0
Bank Sta=9077.878,10922.07
Exp/Cntr=0.3,0.1

Type RM Length L Ch R = 1 ,3018.321,255.676200,255.676200,255.676200
XS GIS Cut Line= 4
1245186.77365011615520.1568468811245121.83451864615881.218417794
1245153.00530177616218.9019013791245062.09051773616889.073738039
#Sta/Elev= 30
9474.23585.331339515.14984.455319555.15180.702649631.82171.964749675.15664.56435
9708.49161.437949718.49158.642499795.16151.499829914.30650.2145410006.5642.85485
10026.3349.8008910092.2253.9605810135.0653.0599210181.19 55.520710207.6852.66299
 10277.252.0076210340.1152.7110710356.6754.5081510379.8453.35641 10396.455.11352
10442.7553.2808910479.1754.81404 10518.957.9857110578.4970.3857110608.2973.59571
10621.5472.7443710681.1376.8317910744.0482.8668910770.5388.4585110856.5290.95743
#Mann= 3 , 0 , 0
9474.235  0.0909       09474.235  0.0909       010856.52  0.0909       0
#XS Ineff= 2 , 0
       0                10164.05       0
Bank Sta=9474.235,10856.52
Exp/Cntr=0.3,0.1

Type RM Length L Ch R = 1 ,2762.645,246.691200,246.691200,246.691200
XS GIS Cut Line= 6
1244944.41739578 615533.025664671244938.15455219615846.289114103
 1244890.9954786616005.8426075011244862.67718855616310.161046697
1244829.32358665616515.8560484311244736.62126645616852.888833842
#Sta/Elev= 30
9585.73669.430679626.26167.262829793.61351.085169902.32747.734959922.44448.93391
9959.76246.343359991.11141.7160310012.3140.8338310026.3942.0727910046.8149.28109
10073.5847.7797410119.6751.2056110152.5948.6414310208.5650.0505410221.7252.43358
 10231.650.6981510248.0652.6812210304.1150.1154710416.56 51.938610469.6150.55777
10606.4455.5507210636.6752.9515910670.2657.5624710731.2858.1952710782.1960.43928
10823.2663.7148910836.9863.0768910854.1366.0529710899.1666.9744110930.1469.88221
#Mann= 3 , 0 , 0
9585.736  0.0673       09585.736  0.0673       010930.14  0.0673       0
#XS Ineff= 2 , 0
       0                10189.33       0
Bank Sta=9585.736,10930.14
Exp/Cntr=0.3,0.1

Type RM Length L Ch R = 1 ,2515.954,145.785400,145.785400,145.785400
XS GIS Cut Line= 4
1244797.13886136615499.3763248181244729.60216463615842.254938915
1244703.62651205616166.9505962281244584.13851017616826.732171819
#Sta/Elev= 30
9487.381 63.61389566.32260.893969619.82456.054219763.61147.564919939.20145.43934
10005.03  40.83610034.6546.1807610080.7349.7074310100.4847.3365110143.2646.88298
10183.0250.2712610213.0348.7969510246.3749.5359710263.0451.9842210303.0551.29783
10393.08 55.137410436.4254.7005410459.76 55.8127 10473.154.6290710519.7853.82862
10536.4555.4221110589.7955.6375410626.4757.7688410639.8156.1746510659.8155.87338
10676.4859.1918810703.1673.84464 10726.575.0239710753.1780.5022110833.0988.27595
#Mann= 3 , 0 , 0
9487.381  0.0994       09487.381  0.0994       010833.09  0.0994       0
#XS Ineff= 2 , 0
       0                10089.42       0
Bank Sta=9487.381,10833.09
Exp/Cntr=0.3,0.1

Type RM Length L Ch R = 1 ,2370.169,196.238400,196.238400,196.238400
XS GIS Cut Line= 6
1244591.65483359615631.7623598921244574.32742266 615848.32249801
1244573.16642638616066.7153272751244537.68792121616265.984233119
1244447.47883776616573.495790591  1244320.635827616880.994518585
#Sta/Elev= 30
9641.86860.108589715.121 56.12369836.89946.390849856.64746.770449909.18943.68576
9974.86243.926429997.848 39.9704 10043.845.0291210060.2249.6548910070.0850.72373
10106.4646.2588710172.7746.8890310219.6945.8604110256.5546.6602310290.1851.71576
10408.9157.5043110473.8555.7628910521.9850.5095910620.3352.7571110636.5454.81141
10650.5458.7431410664.5361.0636310671.5365.0683310692.5372.7829810724.1590.31376
10763.0698.7799210787.93102.105410841.46105.680510913.25108.486310933.58106.6095
#Mann= 3 , 0 , 0
9641.868   0.088       09641.868   0.088       010933.58   0.088       0
#XS Ineff= 2 , 0
       0                10077.55       0
Bank Sta=9641.868,10933.58
Exp/Cntr=0.3,0.1