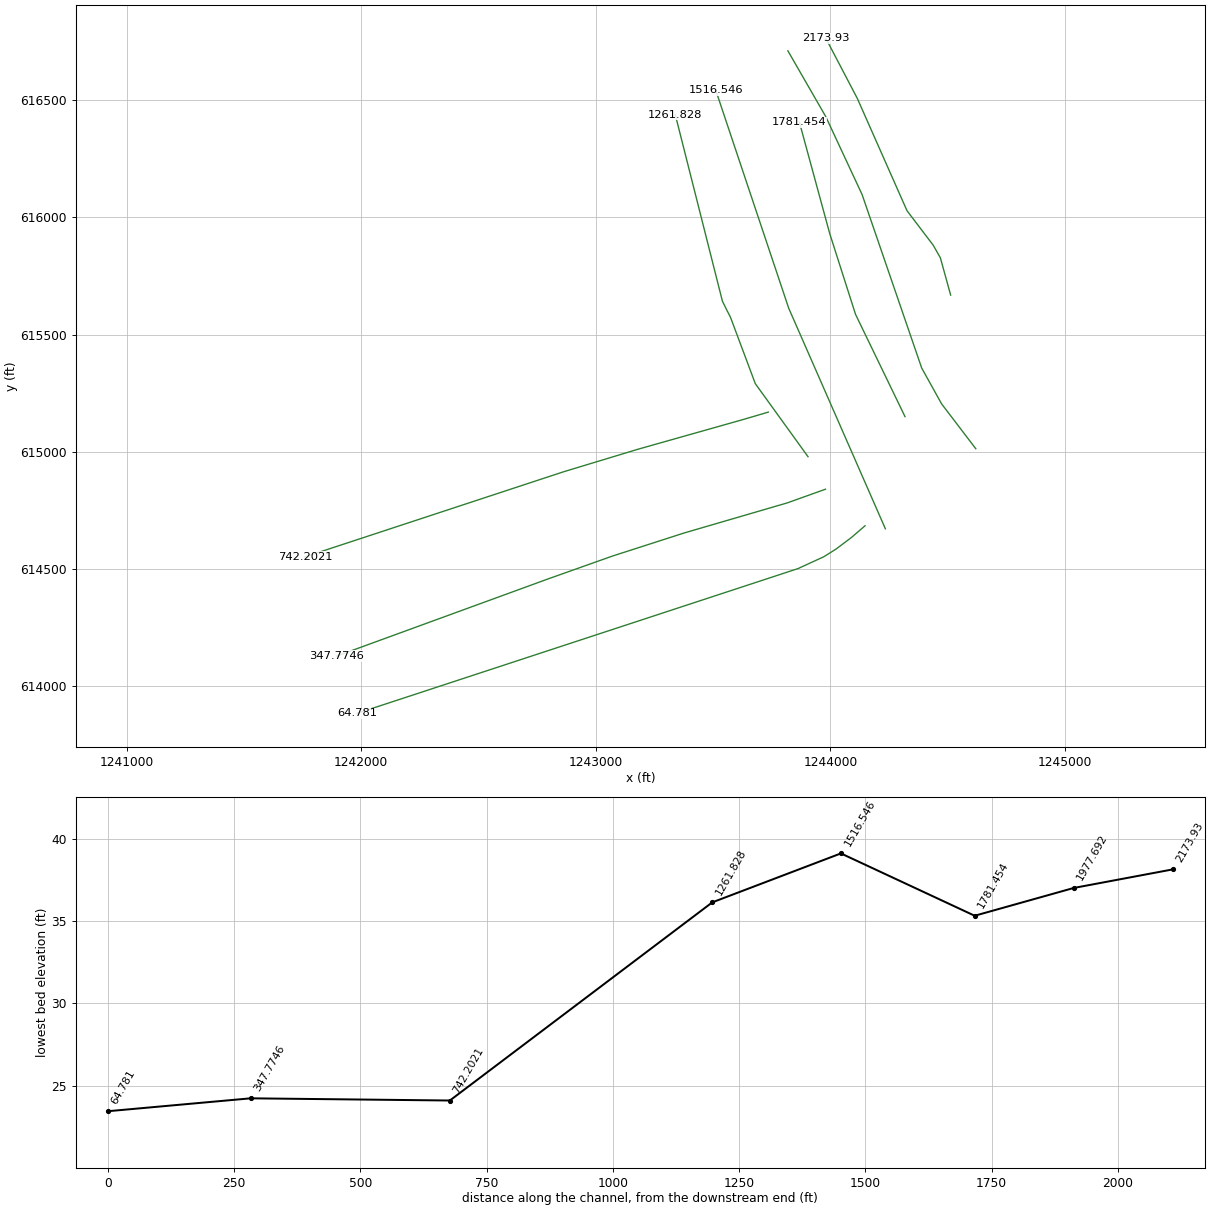
HEC-RAS study 426_ras.prj: 426

--- 426_ras.g01 (geometry) --- (continued)

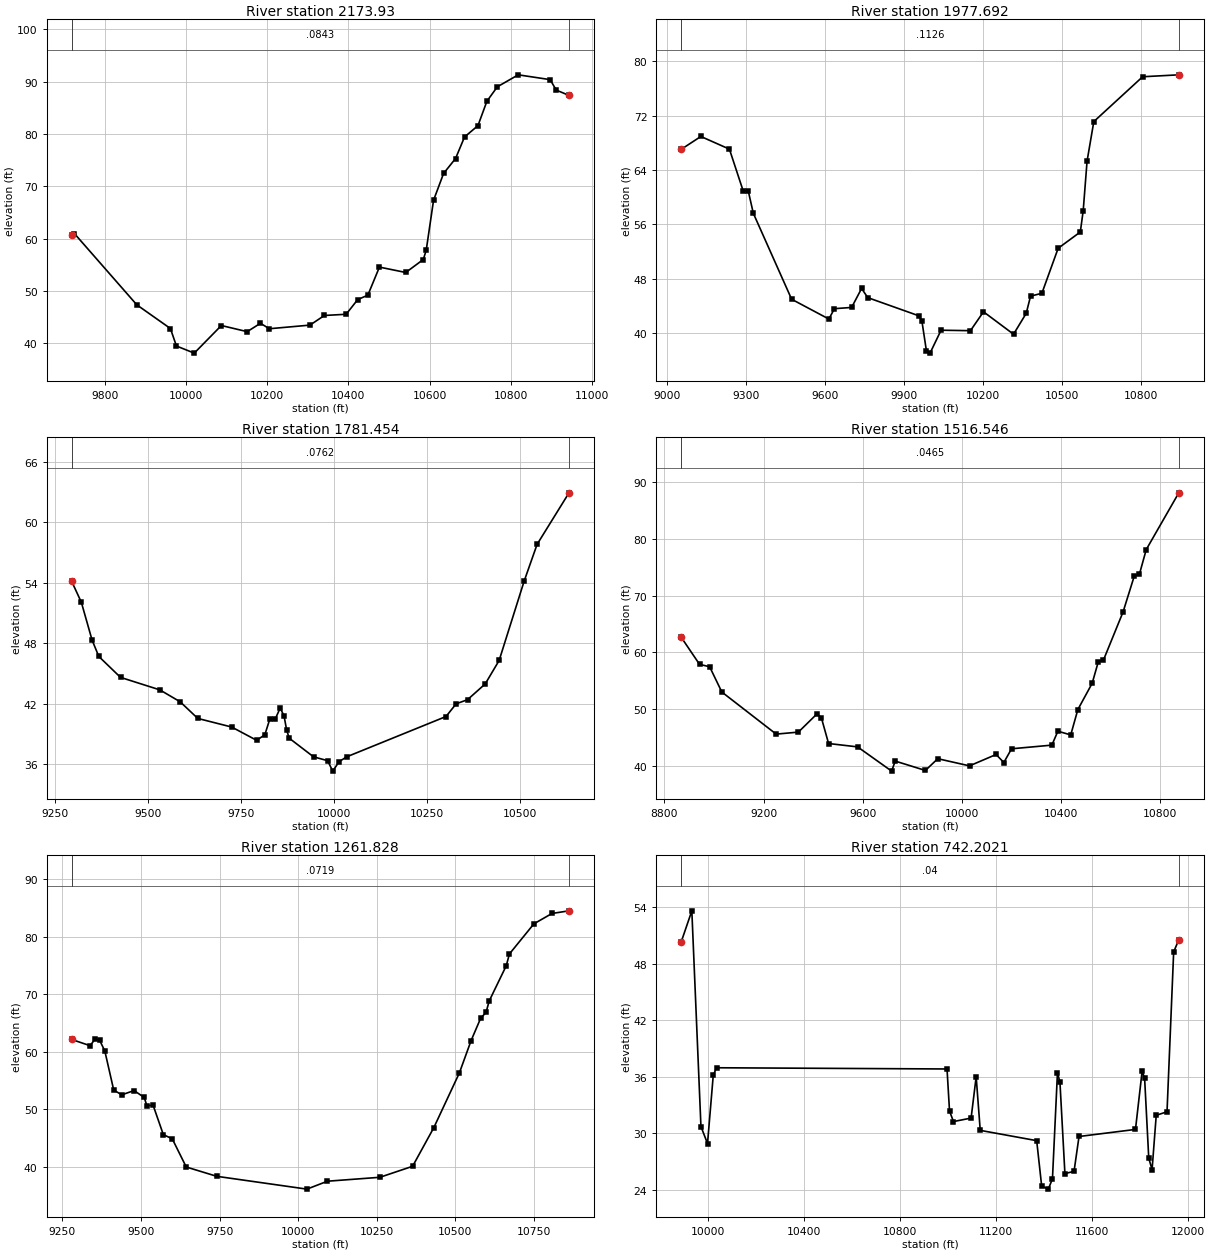
Type RM Length L Ch R = 1 , 2173.93,196.238300,196.238300,196.238300
XS GIS Cut Line= 6
1244512.15741183615668.1986781991244468.41928883615826.714431663
1244438.08745664615880.300491954 1244326.1680945616027.624023348
1244114.41641739616506.1395286621243980.23439803 616762.49807517
#Sta/Elev= 30
9718.60660.697969725.79360.973139879.33247.369549962.01842.847929976.88139.50411
10020.7938.1430710087.5143.4181910151.0942.2447110183.8143.8445210205.6242.80237
 10305.643.4948110341.2545.3384110394.7145.5646910423.2348.3707110448.1849.21438
 10476.754.5788910541.5253.5483110584.7456.0295710591.94 57.815110609.9567.34186
10634.6272.4668710664.1775.3243510686.2179.4321810719.28 81.600710741.3286.26565
10767.04 89.022510818.4791.30928   1089790.3929210912.0188.3963810943.4987.37619
#Mann= 3 , 0 , 0
9718.606  0.0843       09718.606  0.0843       010943.49  0.0843       0
#XS Ineff= 2 , 0
       0                10195.13       0
Bank Sta=9718.606,10943.49
Exp/Cntr=0.3,0.1

Type RM Length L Ch R = 1 ,1977.692,196.238300,196.238300,196.238300
XS GIS Cut Line= 6
1244619.17308236615013.4119150711244473.58926198615204.407022194
1244388.75497823615357.0717688261244134.68547697616096.636045733
 1243979.8439643616428.8130039831243818.32780048616709.311350493
#Sta/Elev= 30
  9055.967.041169129.97168.923799238.39967.057939290.58760.90619 9309.7660.93262
9329.02557.619769474.50144.951339615.93142.034259636.86543.560629702.25843.74424
9740.10546.541579763.38245.190179958.66842.493929968.908 41.75619985.975  37.389
9999.90437.0146210041.6940.3893510153.2340.3199910202.7243.1037510316.7839.80006
10364.8942.8742610381.3845.4056110424.4445.8306710486.1152.4564910570.2554.85592
10581.2358.0049310595.8665.2902510621.4971.1163310806.7977.7186410944.0778.00285
#Mann= 3 , 0 , 0
  9055.9  0.1126       0  9055.9  0.1126       010944.07  0.1126       0
#XS Ineff= 2 , 0
       09859.091        10165.72       0
Bank Sta=9055.9,10944.07
Exp/Cntr=0.3,0.1

Type RM Length L Ch R = 1 ,1781.454,264.907400,264.907400,264.907400
XS GIS Cut Line= 4
 1244317.6434702615149.941779763 1244106.8066121 615585.78940244
 1243996.9588373615929.5066333411243867.62194109616404.332498699
#Sta/Elev= 30
9294.58354.179199320.92652.072639349.67248.336769367.89546.699819426.20844.62549
9531.89943.385969586.56742.202959633.94640.55162 9725.0639.69903 9792.0438.38423
9814.11738.929179827.89440.535919841.67240.465619855.44941.584669865.78240.79547
 9872.6739.420339879.55938.594819945.00136.745279982.88836.362299996.66535.32608
10013.8936.2735610034.5536.7510910301.1240.7433510328.32 42.001810358.9342.41153
10406.5343.9770210443.9446.30598   1051154.1567810545.9557.8210810631.72 62.9297
#Mann= 3 , 0 , 0
9294.583  0.0762       09294.583  0.0762       010631.72  0.0762       0
#XS Ineff= 2 , 0
       0 9880.92        10100.47       0
Bank Sta=9294.583,10631.72
Exp/Cntr=0.3,0.1

Type RM Length L Ch R = 1 ,1516.546,254.718400,254.718400,254.718400
XS GIS Cut Line= 3
1244233.89942157614672.066621184 1243821.8484498615612.292020485
1243510.93726197616541.279666036
#Sta/Elev= 30
8868.08962.648878941.41757.919328982.28557.486019031.32653.045039250.55445.62786
9340.10545.983579415.32949.198229433.23948.446779461.89543.973759578.95943.38108
9716.22239.11271 9730.5540.88096 9852.3439.231369902.22141.3009810030.2340.03913
10137.4842.0415510168.6240.6259210199.7643.0463910362.3643.6896910386.5846.14137
10438.4745.4901610467.1149.9510210524.9754.5863410549.18 58.305810570.4858.67355
10649.5267.1417110694.5373.43766 10715.273.7407310742.9378.1200610874.2888.11323
#Mann= 3 , 0 , 0
8868.089  0.0465       08868.089  0.0465       010874.28  0.0465       0
#XS Ineff= 2 , 0
       09887.232        10115.05       0
Bank Sta=8868.089,10874.28
Exp/Cntr=0.3,0.1

Type RM Length L Ch R = 1 ,1261.828,519.625700,519.625700,519.625700
XS GIS Cut Line= 6
1243904.25864413614979.2318910661243679.53276533615290.554294884
1243573.60795763615573.7667559531243558.33663541615603.519859076
1243539.28398266615642.2179770771243338.62503737616436.393964112
#Sta/Elev= 30
9279.22662.138529338.06561.056059354.88162.239979368.84461.966719385.02960.13446
9413.35353.345599438.96452.517779478.09453.257069510.46452.056939518.557 50.6567
9538.78850.683839571.15845.601459599.482 44.88039643.99139.981979741.14538.36279
10027.7536.1393110093.1337.51496 10259.8 38.195210363.8540.1069310431.5246.83766
10512.7456.3360210549.9661.9478710580.4265.8354310597.3466.8213710607.4968.82353
10661.6374.9291910671.7876.9866710749.6182.2169410807.1484.0156710861.2784.47521
#Mann= 3 , 0 , 0
9279.226  0.0719       09279.226  0.0719       010861.27  0.0719       0
#XS Ineff= 2 , 0
       0 9903.35        10158.22       0
Bank Sta=9279.226,10861.27
Exp/Cntr=0.3,0.1

Type RM Length L Ch R = 1 ,742.2021,394.427500,394.427500,394.427500
XS GIS Cut Line= 6
1243734.80857173615169.2644119871243732.13538545615168.419177443
1243629.37356925615138.1945844741243179.24644569615011.018374681
1242861.01674232614914.5799958411241759.61061645614552.193607897
#Sta/Elev= 30
9891.08250.337269934.75453.592469972.65730.7359910000.0128.9366410023.8836.17054
10037.5236.9636410996.47 36.835211006.8332.3840611023.2531.2627511096.6331.63358
11117.7236.0075711134.6230.3301411369.4829.2397311390.2124.4249911417.8424.10395
11435.1125.2025411455.8336.4062311466.1935.4729811486.9125.7452111524.9125.99077
11545.6329.6805911780.4930.4303211808.12   36.5911818.4835.8768811835.7527.37735
11849.5726.1755311866.8431.9257611911.7432.2999911939.3749.2343411960.7650.53735
#Mann= 3 , 0 , 0
9891.082    0.04       09891.082    0.04       011960.76    0.04       0
#XS Ineff= 2 , 0
       0                10582.95       0
Bank Sta=9891.082,11960.76
Exp/Cntr=0.3,0.1

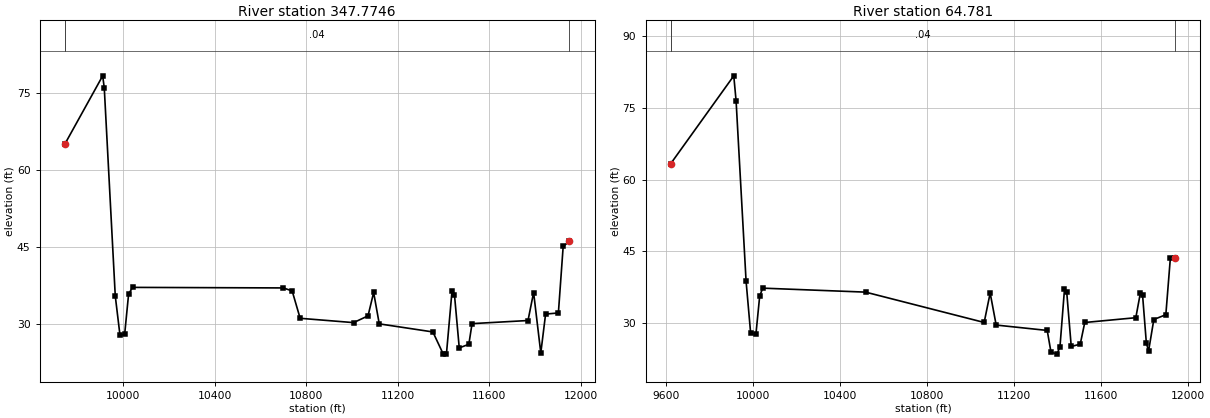
Type RM Length L Ch R = 1 ,347.7746,282.993600,282.993600,282.993600
XS GIS Cut Line= 6
1243978.67941067614840.6888854651243815.90554276614782.418108672
1243375.62484789614653.9554395381243068.92005226614555.169701621
1242793.29791042614457.2541303631241895.44320992614129.512069613
#Sta/Elev= 30
9747.09465.09236  9911.6 78.29289918.52675.924099966.50635.528229987.06227.91356
10007.5928.1339910024.6735.8802110041.7537.2008210700.51 37.0952 10738.836.51114
10773.6231.1966611006.97 30.357511070.0231.6737411094.5336.2078911119.0530.11622
11353.1228.5469411398.49 24.237311412.4524.3343811436.8836.5872711447.3535.78923
11468.2925.4439311510.1726.1531311524.1430.1606311768.4530.7647611792.8836.20591
11824.2924.4650811845.2332.0135311901.0832.2366111922.0245.1836311949.2146.12399
#Mann= 3 , 0 , 0
9747.094    0.04       09747.094    0.04       011949.21    0.04       0
#XS Ineff= 2 , 0
       0                10591.46       0
Bank Sta=9747.094,11949.21
Exp/Cntr=0.3,0.1

Type RM Length L Ch R = 1 ,  64.781,0.000000,0.000000,0.000000
XS GIS Cut Line= 6
1244147.23911292614684.7711608621244089.04462365614634.711668826
1244023.49214843614585.411657249 1243971.2929869614552.664047704
1243861.46209752614502.3212575841241981.94392818613885.193672776
#Sta/Elev= 30
9620.36163.361119910.08181.745969920.72376.527089966.72838.709329987.55827.90418
10011.8627.58482 10029.235.5758710043.0237.2734810516.0636.4396811061.5530.08543
11089.1736.2523411116.78 29.543411351.5528.4144911368.8123.8881711396.4323.45275
11410.2425.0085511430.96 37.051811441.3136.3878811462.0325.0519311503.4625.54304
11524.1730.0783511758.9431.0823911779.6536.1851911790.0135.8343411807.2725.86275
11817.5824.07752 11841.830.7056211897.0331.7111211917.7543.5361511939.9443.52498
#Mann= 3 , 0 , 0
9620.361    0.04       09620.361    0.04       011939.94    0.04       0
#XS Ineff= 2 , 0
       0                10324.09       0
Bank Sta=9620.361,11939.94
Exp/Cntr=0.3,0.1